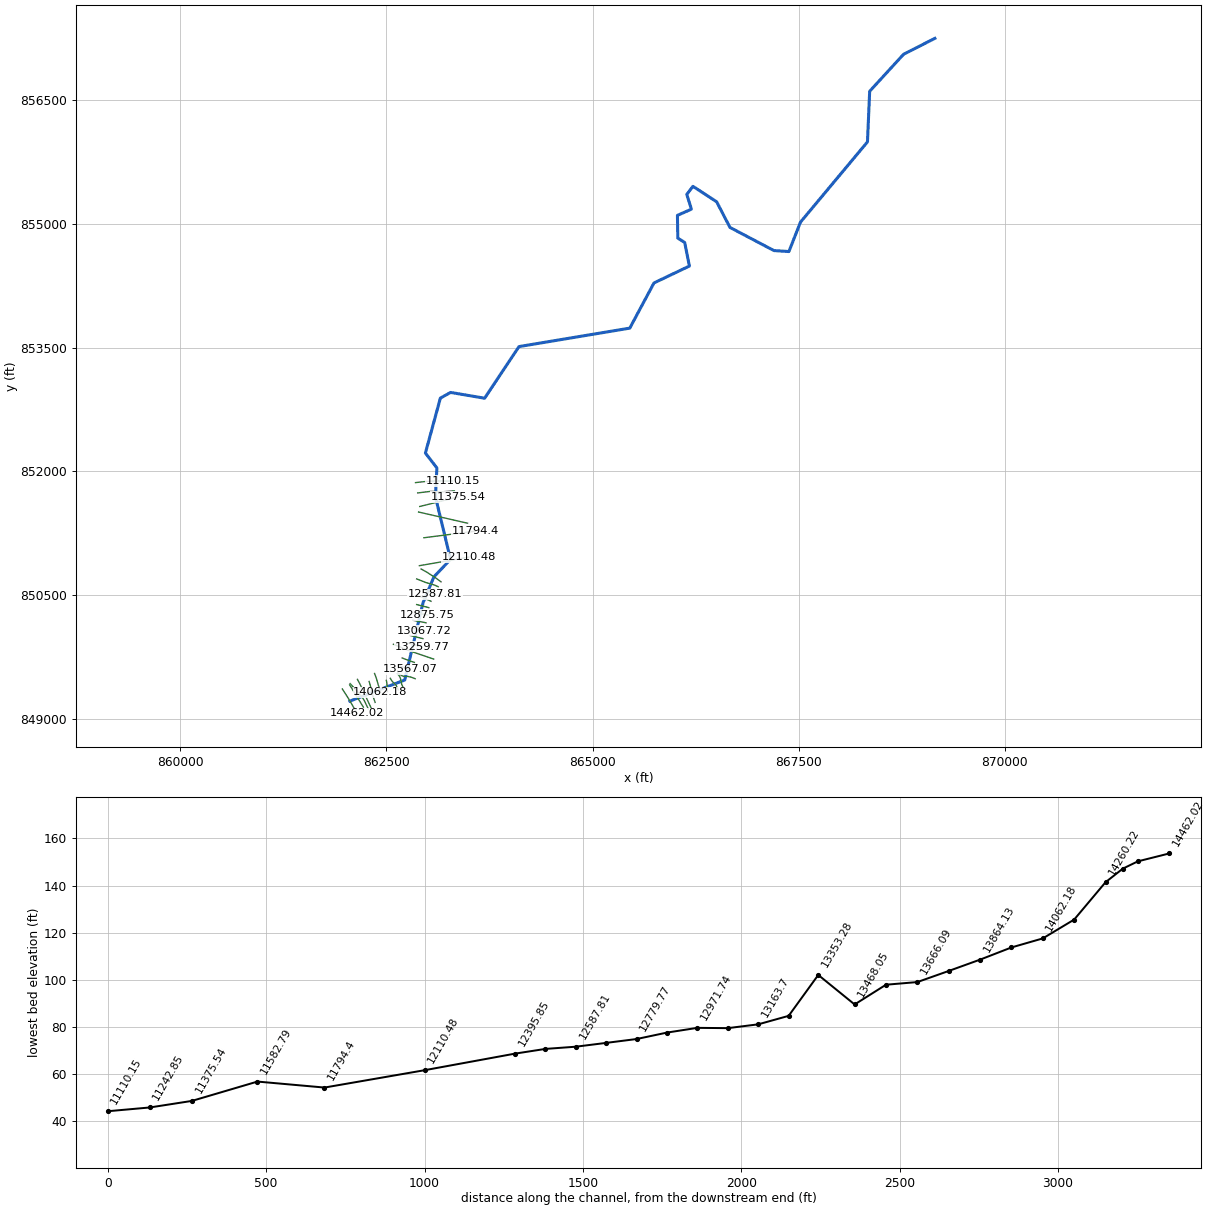
--- 16979_ras.prj (project) ---

Proj Title=16979
Current Plan=p01
Default Exp/Contr=0.3,0.1
English Units
Geom File=g01
Flow File=f01
Plan File=p01
Y Axis Title=Elevation
X Axis Title(PF)=Main Channel Distance
X Axis Title(XS)=Station
BEGIN DESCRIPTION:
RFD model 16979 exported to HEC-RAS
END DESCRIPTION:

--- 16979_ras.p01 (plan) ---

Plan Title=Plan 01
Program Version=4.10
Short Identifier=Plan 01
Geom File=g01
Flow File=f01
Subcritical Flow
Calc Critical at every XS
Secant Critical Depth

--- 16979_ras.f01 (steady flow) ---

Flow Title=Flow 01
Program Version=5.01
Number of Profiles= 6
Profile Names=10yr,25yr,50yr,100yr,100plus,500yr
River Rch & RM=16979,56,14462.02
  179.07  281.04  374.65  458.03  668.73 1130.34
River Rch & RM=16979,56,12587.81
  181.63  285.11  380.12  464.76  678.54 1144.76
River Rch & RM=16979,56,12491.83
  190.54  299.24  399.12  488.11  712.65 1194.66
River Rch & RM=16979,56,12110.48
  206.89  325.36  434.36  531.61  776.15 1287.52
River Rch & RM=16979,56, 11794.4
  212.83   334.9  447.28   547.6   799.5 1321.67
River Rch & RM=16979,56,11582.79
  217.94   343.1   458.4  561.38  819.61 1350.98
River Rch & RM=16979,56,11375.54
  239.26  377.21  504.48  618.29   902.7  1470.2
River Rch & RM=16979,56,11242.85
  241.17  380.28  508.65  623.46  910.25 1481.05
River Rch & RM=16979,56,11110.15
  243.11   383.4  512.86  628.66  917.84 1491.86
River Rch & RM=16979,56,10977.46
  245.02  386.46  517.02  633.81  925.37 1502.64
River Rch & RM=16979,56,10844.76
  247.33  390.17  522.03  640.01  934.42 1515.54
River Rch & RM=16979,56,10712.07
  250.42  395.12  528.72  648.29   946.5 1532.67
River Rch & RM=16979,56,10579.37
  559.86  888.37 1194.02 1468.09 2143.41 3108.71
River Rch & RM=16979,56,10446.68
  564.93  896.57 1205.19 1481.97 2163.67 3134.56
River Rch & RM=16979,56,9999.026
  573.09  909.79 1223.22 1504.39 2196.41  3176.4
River Rch & RM=16979,56,9897.426
  578.97  919.36 1236.28 1520.67 2220.18 3206.84
River Rch & RM=16979,56,9433.862
  614.81  977.39 1315.37 1618.99 2363.72 3388.71
River Rch & RM=16979,56,9034.249
  631.79 1005.01 1353.15 1666.09 2432.49  3475.9
River Rch & RM=16979,56,8678.391
  736.63 1175.02  1585.1 1954.67 2853.81 3999.94
River Rch & RM=16979,56,7219.576
  850.71 1361.59 1841.08 2274.68 3321.03 4574.96
River Rch & RM=16979,56,6918.643
  856.23 1370.64 1853.52 2290.26 3343.77 4602.74
River Rch & RM=16979,56,6588.603
  879.58 1409.06 1906.45 2356.66 3440.72 4721.46
River Rch & RM=16979,56,6506.232
  882.55 1413.96  1913.2 2365.12 3453.08 4736.56
River Rch & RM=16979,56,6161.233
  900.05 1442.65 1952.63  2414.5 3525.17 4824.04
River Rch & RM=16979,56,5832.239
   914.6 1466.59 1985.59 2455.84 3585.53 4897.38
River Rch & RM=16979,56,5353.895
  944.52 1515.97 2053.75 2541.48 3710.56 5049.45
River Rch & RM=16979,56, 4857.99
  945.05 1516.84 2054.95 2542.99 3712.76 5052.13
River Rch & RM=16979,56,4455.802
  954.77 1532.89 2077.11 2570.85 3753.45 5101.52
River Rch & RM=16979,56,3977.377
  956.61 1535.93 2081.31 2576.13 3761.15 5110.85
River Rch & RM=16979,56,1664.071
  954.77 1532.89 2077.11 2570.85 3753.45 5101.52
Boundary for River Rch & Prof#=16979,56,1
Up Type= 0
Dn Type= 2
Boundary for River Rch & Prof#=16979,56,2
Up Type= 0
Dn Type= 2
Boundary for River Rch & Prof#=16979,56,2
Up Type= 0
Dn Type= 2
Boundary for River Rch & Prof#=16979,56,2
Up Type= 0
Dn Type= 2
Boundary for River Rch & Prof#=16979,56,2
Up Type= 0
Dn Type= 2
Boundary for River Rch & Prof#=16979,56,2
Up Type= 0
Dn Type= 2

--- 16979_ras.g01 (geometry) ---

Geom Title=16979
Program Version=4.10

River Reach=16979,56
Reach XY= 30
862057.752663791849213.567115381862722.293400943849468.867279202
862945.190309137850407.521187603863076.718261063850720.125005096
 863278.14639625850931.897457391  863095.2826837 851688.61547707
863112.243754447852040.866231784862973.336185932852220.737766191
863154.866776496852887.224192113863278.330525875852956.213996917
863691.251528203852885.900950417 864107.87522319853511.875483721
865451.630897284  853735.7956222865745.042787969854283.767442137
866174.319152117854488.467939362866117.337284148 854774.54893291
866033.935618341854826.694347307866029.531254679855103.150894791
866198.951951116855178.176332146866142.604698956855357.375917301
866217.611040115855455.323364019866505.151069671855267.724861398
 866666.18305999854957.194322556867199.341751128854676.453485742
867381.141014278854664.299107149867521.375287116855020.899859771
868333.785198003855994.047678679  868360.4977009856608.247513026
868771.590378076857056.405166417 869151.17321074857249.853986293

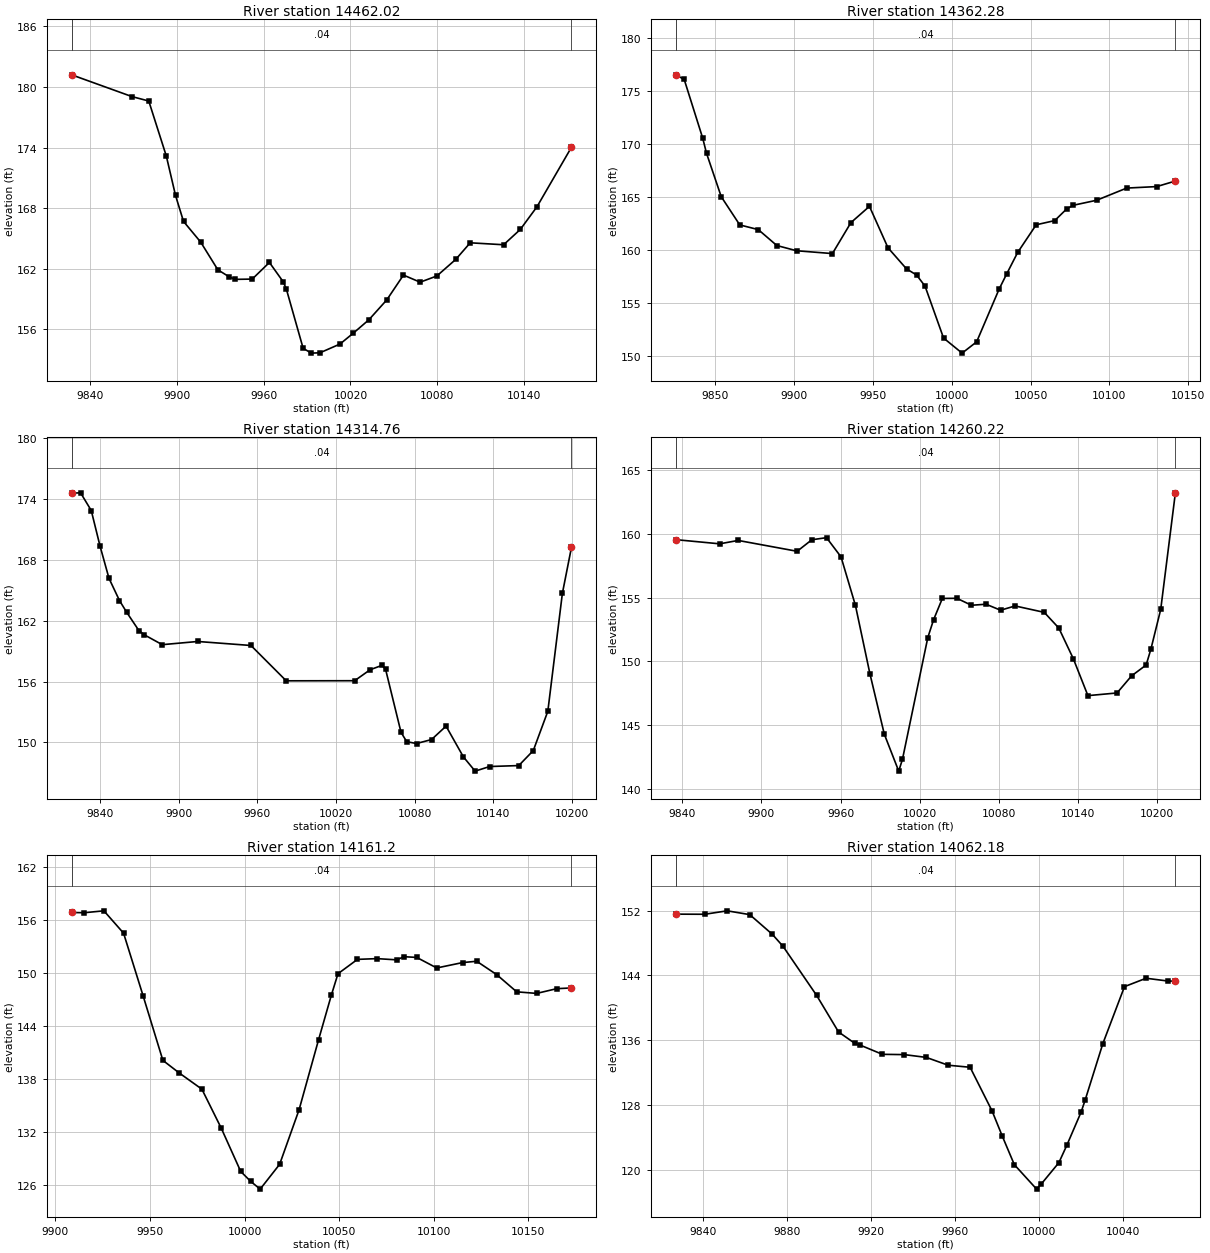
Type RM Length L Ch R = 1 ,14462.02,99.737800,99.737800,99.737800
XS GIS Cut Line= 5
861966.183957979849360.098528675862040.928121331849243.688227226
862058.106541485849214.936337993862059.121886393849213.213237671
862144.988362169849064.352679469
#Sta/Elev= 30
9827.167181.20999868.877179.05349880.501178.61369892.645173.1584 9899.01169.2567
9904.529166.68339916.413164.63299928.297161.88549936.027161.19899940.181160.9394
9952.064160.96789963.948162.61459973.446160.70879975.628159.99749987.277154.1059
9992.943 153.6299998.926153.663210012.76154.528710022.03155.614810032.78156.9381
10045.11158.902810056.66161.3631 10068.2160.660310079.75161.274610092.82162.9165
10102.84164.562810125.93164.368910137.47 165.88510149.01168.134110172.85174.0291
#Mann= 3 , 0 , 0
9827.167    0.04       09827.167    0.04       010172.85    0.04       0
#XS Ineff= 2 , 0
       0                10081.46       0
Bank Sta=9827.167,10172.85
Exp/Cntr=0.3,0.1

Type RM Length L Ch R = 1 ,14362.28,47.525700,47.525700,47.525700
XS GIS Cut Line= 2
 862054.69850025849409.640752692862221.222472468849139.861198191
#Sta/Elev= 30
9824.837176.49819830.291176.06579842.042170.52369844.449169.10359853.794165.0079
9865.546162.35189877.297 161.9089889.049160.40899901.565159.91649924.304159.6493
9936.055162.56829947.807164.10179959.559160.1981 9971.31158.20729977.718157.6268
9983.062156.58099994.814151.688810006.57150.2662 10015.8  151.3310030.07156.3051
10034.83157.724310041.82159.753610053.57162.363610065.32162.756910072.91163.8576
10077.07164.202510091.95164.676510110.99165.823810130.03165.963810141.87166.4886
#Mann= 3 , 0 , 0
9824.837    0.04       09824.837    0.04       010141.87    0.04       0
#XS Ineff= 2 , 0
       09943.067        10075.03       0
Bank Sta=9824.837,10141.87
Exp/Cntr=0.3,0.1

Type RM Length L Ch R = 1 ,14314.76,54.541500,54.541500,54.541500
XS GIS Cut Line= 5
862060.414165894849426.042265815 862162.63913148849313.986520236
862199.034125773849272.819422316862232.170988192849219.845964141
862280.627999584849118.756045106
#Sta/Elev= 30
9818.315174.5938 9825.12174.62649833.262 172.8819839.958 169.3759846.798 166.189
9854.795163.99969860.334162.83169869.633 161.032 9873.87160.60889887.406159.6461
9914.478159.96049955.086159.56539981.989156.080410034.17156.089910045.96157.1718
10055.05157.606710057.76157.219310069.55150.9952 10073.9 150.07410081.35149.8938
 10092.8150.283510103.89151.608310117.11148.578410126.07147.170210137.16147.6245
10159.34147.717910170.43149.197810181.52153.075410192.61164.701510199.53169.2353
#Mann= 3 , 0 , 0
9818.315    0.04       09818.315    0.04       010199.53    0.04       0
#XS Ineff= 2 , 0
       09947.811        10022.24       0
Bank Sta=9818.315,10199.53
Exp/Cntr=0.3,0.1

Type RM Length L Ch R = 1 ,14260.22,99.020700,99.020700,99.020700
XS GIS Cut Line= 6
   862149.208401849476.857434709862175.760414297849427.235487515
862202.980732172849371.918009665862224.883560793849322.657050347
862225.716872686849320.838921005862312.881251388849134.916146579
#Sta/Elev= 30
 9834.83159.54069868.302159.21279882.303 159.4789927.036158.62819938.181159.5309
9949.326 159.6959960.332158.19099971.276154.3862 9982.22149.05989993.164144.3145
10004.11141.417210006.95142.344610026.17151.869310030.54153.264710037.21154.9368
10048.25154.9469 10059.3154.402210070.34154.484310081.39154.015810092.43154.3489
10114.52153.847510125.57  152.6210136.61150.210510147.65 147.32810169.74147.5367
10180.79148.876610191.83149.725810195.45150.973610202.88154.075310214.01163.2054
#Mann= 3 , 0 , 0
 9834.83    0.04       0 9834.83    0.04       010214.01    0.04       0
#XS Ineff= 2 , 0
       09945.517        10029.24       0
Bank Sta=9834.83,10214.01
Exp/Cntr=0.3,0.1

Type RM Length L Ch R = 1 , 14161.2,99.020700,99.020700,99.020700
XS GIS Cut Line= 6
862290.840221356 849451.33159568862296.168879247849433.524725713
862306.534255779849396.657804772862314.480517055849362.066723472
862331.300485433849292.288375662862363.581247302849197.611085214
#Sta/Elev= 30
9908.625156.90119915.234 156.8749925.672157.08849936.067154.55919946.455147.4257
9956.842140.16169965.508138.7313 9977.47136.9004 9987.73132.47279997.991127.5874
10003.22126.472310008.27 125.58710018.56128.392910028.84134.572310039.13 142.484
10045.89147.538510049.41149.9696 10059.7151.593210069.99151.678210080.48151.5394
10084.24151.897510091.04151.813710101.61150.620910115.23151.229910122.74151.3808
 10133.3149.867310143.87147.919510154.43147.7411   10165148.275410172.81  148.36
#Mann= 3 , 0 , 0
9908.625    0.04       09908.625    0.04       010172.81    0.04       0
#XS Ineff= 2 , 0
       0                 10063.9       0
Bank Sta=9908.625,10172.81
Exp/Cntr=0.3,0.1

Type RM Length L Ch R = 1 ,14062.18,99.020800,99.020800,99.020800
XS GIS Cut Line= 6
862356.857222845849547.929720871862376.825227638849495.388873449
862402.921604127849406.395762593862411.109461151849382.911006134
862417.778527258849363.218554823862427.878097566849321.481706167
#Sta/Elev= 29
 9827.18151.55489841.012151.5401 9851.71151.96479862.408151.49789873.106149.0771
 9878.25147.58069894.214141.51999904.635137.00799912.439135.58719915.056135.3688
9925.477134.24699935.898134.21049946.319133.86699956.741132.90079967.162132.6488
9977.605127.25299982.482124.12979988.187120.6215 9998.77117.6024   10001118.2382
10009.35 120.86710013.13123.016410019.91127.108910021.79128.559810030.25135.5652
10040.54142.604410050.82143.641110061.11143.298310064.73143.2748
#Mann= 3 , 0 , 0
 9827.18    0.04       0 9827.18    0.04       010064.73    0.04       0
#XS Ineff= 2 , 0
       0                               0
Bank Sta=9827.18,10064.73
Exp/Cntr=0.3,0.1

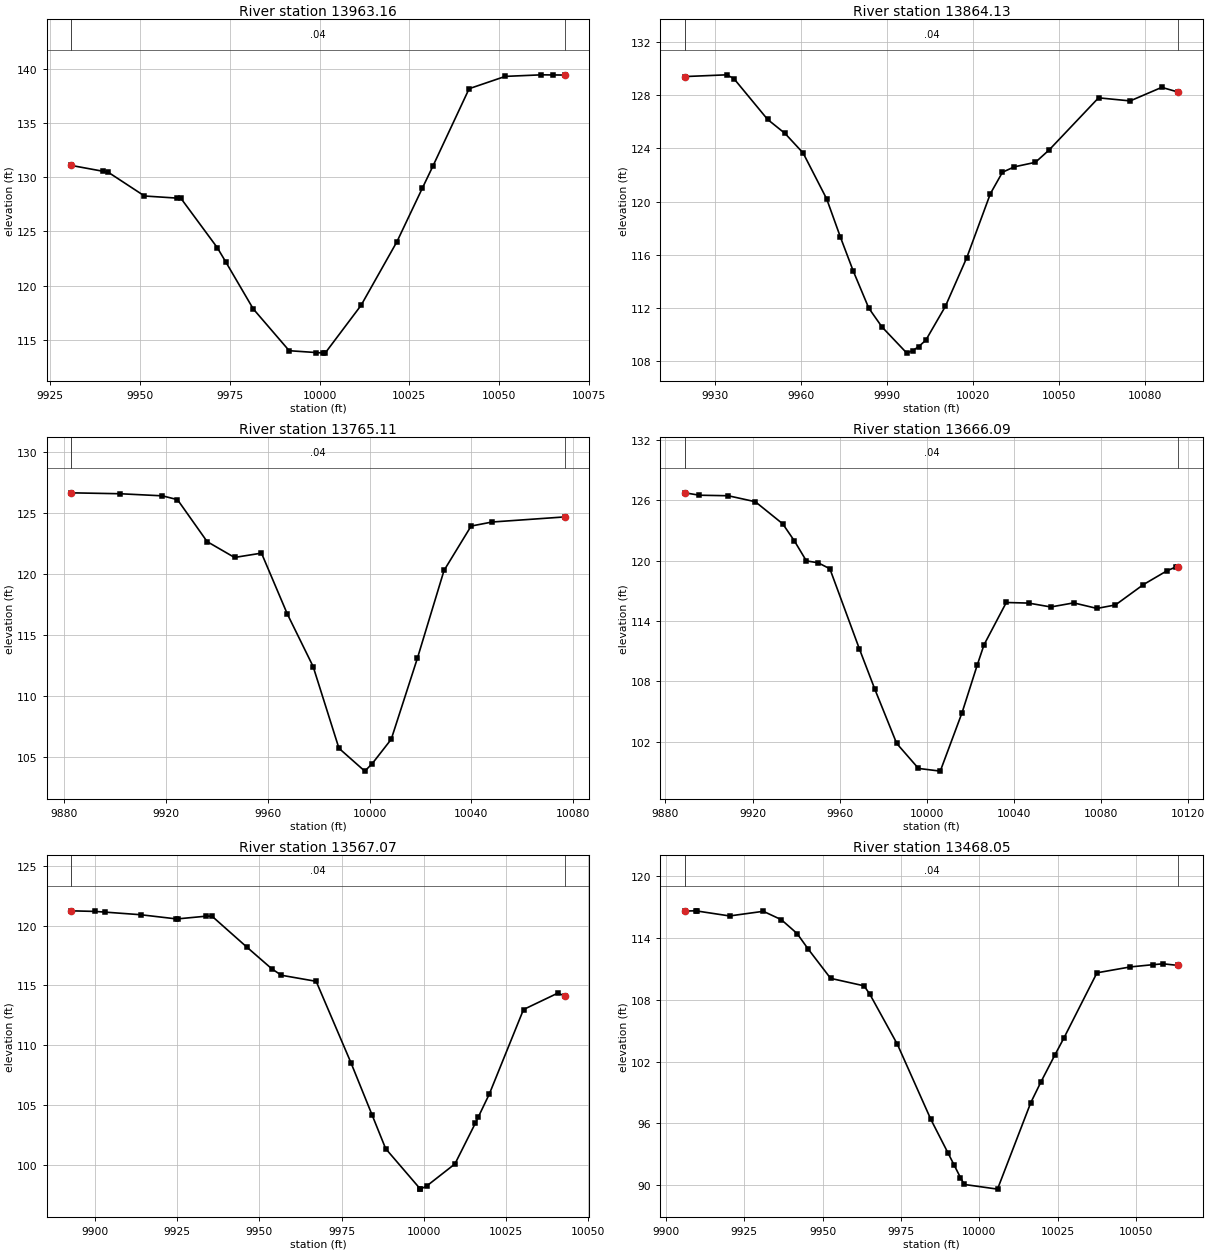
Type RM Length L Ch R = 1 ,13963.16,99.020700,99.020700,99.020700
XS GIS Cut Line= 6
862499.132762465849464.828750893862501.764558911849456.408844417
862507.147119217849422.691206696862509.055754869849367.897975654
862513.222537494849331.682791591862513.841782115849328.619083692
#Sta/Elev= 22
9930.879131.08099939.701 130.5439941.128130.45839951.254 128.2639960.225128.0696
9961.381128.05449971.507123.50739973.845 122.2079981.543 117.8499991.551113.9941
    9999113.8257   10001113.783510001.56113.770810011.56118.174610021.57124.0575
10028.67129.011710031.59131.030810041.66138.159310051.72 139.29410061.79139.4381
10065.13139.426310068.25139.4175
#Mann= 3 , 0 , 0
9930.879    0.04       09930.879    0.04       010068.25    0.04       0
#XS Ineff= 2 , 0
       0                               0
Bank Sta=9930.879,10068.25
Exp/Cntr=0.3,0.1

Type RM Length L Ch R = 1 ,13864.13,99.020800,99.020800,99.020800
XS GIS Cut Line= 6
862547.673955129849489.681358175862565.721029867849459.846203686
862580.906595376849441.579949744862608.611865212 849417.09618752
862619.930109748849401.682288153862643.742208831849349.797340491
#Sta/Elev= 26
9919.585129.40389934.132129.53459936.626129.25799948.396126.18119954.462125.1279
9960.764123.65749968.976120.20329973.768117.32529978.216114.7875 9983.64111.9911
9988.243110.57459996.892108.6079    9999108.8038   10001 109.09610003.49109.5755
 10010.3112.118110017.79115.796710025.99120.5963 10030.2122.209510034.32122.6147
10041.67 122.95510046.47123.887710063.67127.804710074.68127.573210085.68 128.592
 10091.4128.2376
#Mann= 3 , 0 , 0
9919.585    0.04       09919.585    0.04       0 10091.4    0.04       0
#XS Ineff= 2 , 0
       0                               0
Bank Sta=9919.585,10091.4
Exp/Cntr=0.3,0.1

Type RM Length L Ch R = 1 ,13765.11,99.020700,99.020700,99.020700
XS GIS Cut Line= 6
862632.091671039849547.370708471 862651.97400356849524.767383719
862663.450597402849506.694010635862671.002720818849487.647527464
862685.364650256849418.282861253862706.131552366849371.944721311
#Sta/Elev= 18
9882.775126.62629901.859126.55169918.557126.37949924.483 126.0679936.144122.6248
9946.901 121.3269957.497121.68129967.644116.69229977.791 112.3829987.938105.6776
9998.085103.8045   10001104.416510008.48106.4161 10018.8113.085310029.23120.2609
10039.87123.900910048.07124.231610076.61124.6503
#Mann= 3 , 0 , 0
9882.775    0.04       09882.775    0.04       010076.61    0.04       0
#XS Ineff= 2 , 0
       0                               0
Bank Sta=9882.775,10076.61
Exp/Cntr=0.3,0.1

Type RM Length L Ch R = 1 ,13666.09,99.020700,99.020700,99.020700
XS GIS Cut Line= 6
862639.921746274849554.959549137862689.771254374849520.043585981
862712.728060808849513.722228083862761.957907683849511.820948412
 862799.06809931 849503.97125579862849.799437836849484.654800124
#Sta/Elev= 27
9888.932126.72499895.627126.48749908.811 126.4359921.255125.84229933.843123.6487
9939.181121.95939944.702 119.9669950.061119.78369955.485119.18639969.059111.2176
9976.146107.21779986.152101.84839996.15899.3647110006.1799.0969110016.18104.9065
10023.14109.628910026.25111.638310036.47115.837710046.69115.779510056.91115.3934
10067.41115.799310078.09115.249610086.58115.594510099.45117.619610110.14118.9744
10114.59119.393410115.37119.3971
#Mann= 3 , 0 , 0
9888.932    0.04       09888.932    0.04       010115.37    0.04       0
#XS Ineff= 2 , 0
       0                               0
Bank Sta=9888.932,10115.37
Exp/Cntr=0.3,0.1

Type RM Length L Ch R = 1 ,13567.07,99.020700,99.020700,99.020700
XS GIS Cut Line= 6
 862645.64763128849647.892207606862683.321174403849631.591832966
862744.966461005 849610.15904596862746.868145895 849609.53969587
862761.734467933849604.731125214 862787.01517937849597.348973604
#Sta/Elev= 25
9892.686121.2264 9899.97 121.1769902.877121.12039913.773120.90139924.668120.5525
9925.152120.55669933.735120.77859935.513 120.784  9946.1118.20869953.808116.3699
9956.687115.84349967.274115.33489977.861108.54019984.259104.20459988.448101.3534
    999997.982789999.03597.97286   1000198.2446810009.55100.078910015.75103.4721
10016.62103.972110020.03105.922210030.44112.979510040.86114.346210042.96  114.13
#Mann= 3 , 0 , 0
9892.686    0.04       09892.686    0.04       010042.96    0.04       0
#XS Ineff= 2 , 0
       0                               0
Bank Sta=9892.686,10042.96
Exp/Cntr=0.3,0.1

Type RM Length L Ch R = 1 ,13468.05,114.769000,114.769000,114.769000
XS GIS Cut Line= 6
 862691.75829839849736.405273577862728.280313537849721.830615426
862770.085118834849706.350447958862771.965337198849705.668705101
862798.055540436849696.423314922862839.540920906849682.418940389
#Sta/Elev= 27
9906.076116.62829909.566116.64619909.867 116.6329920.333116.1489  9931.1116.5995
9936.847115.78469941.867114.44219945.398112.93679952.564110.08499963.228109.3587
9965.069108.54769973.891103.66139984.55596.372869989.97793.140569991.977 91.9392
9993.97990.731489995.19790.0585810005.8189.6042110016.4298.0051310019.66100.0209
10024.11102.636810026.99104.289610037.54 110.624 10048.1 111.19210055.37111.4131
10058.65111.498110063.44111.3393
#Mann= 3 , 0 , 0
9906.076    0.04       09906.076    0.04       010063.44    0.04       0
#XS Ineff= 2 , 0
       0                               0
Bank Sta=9906.076,10063.44
Exp/Cntr=0.3,0.1

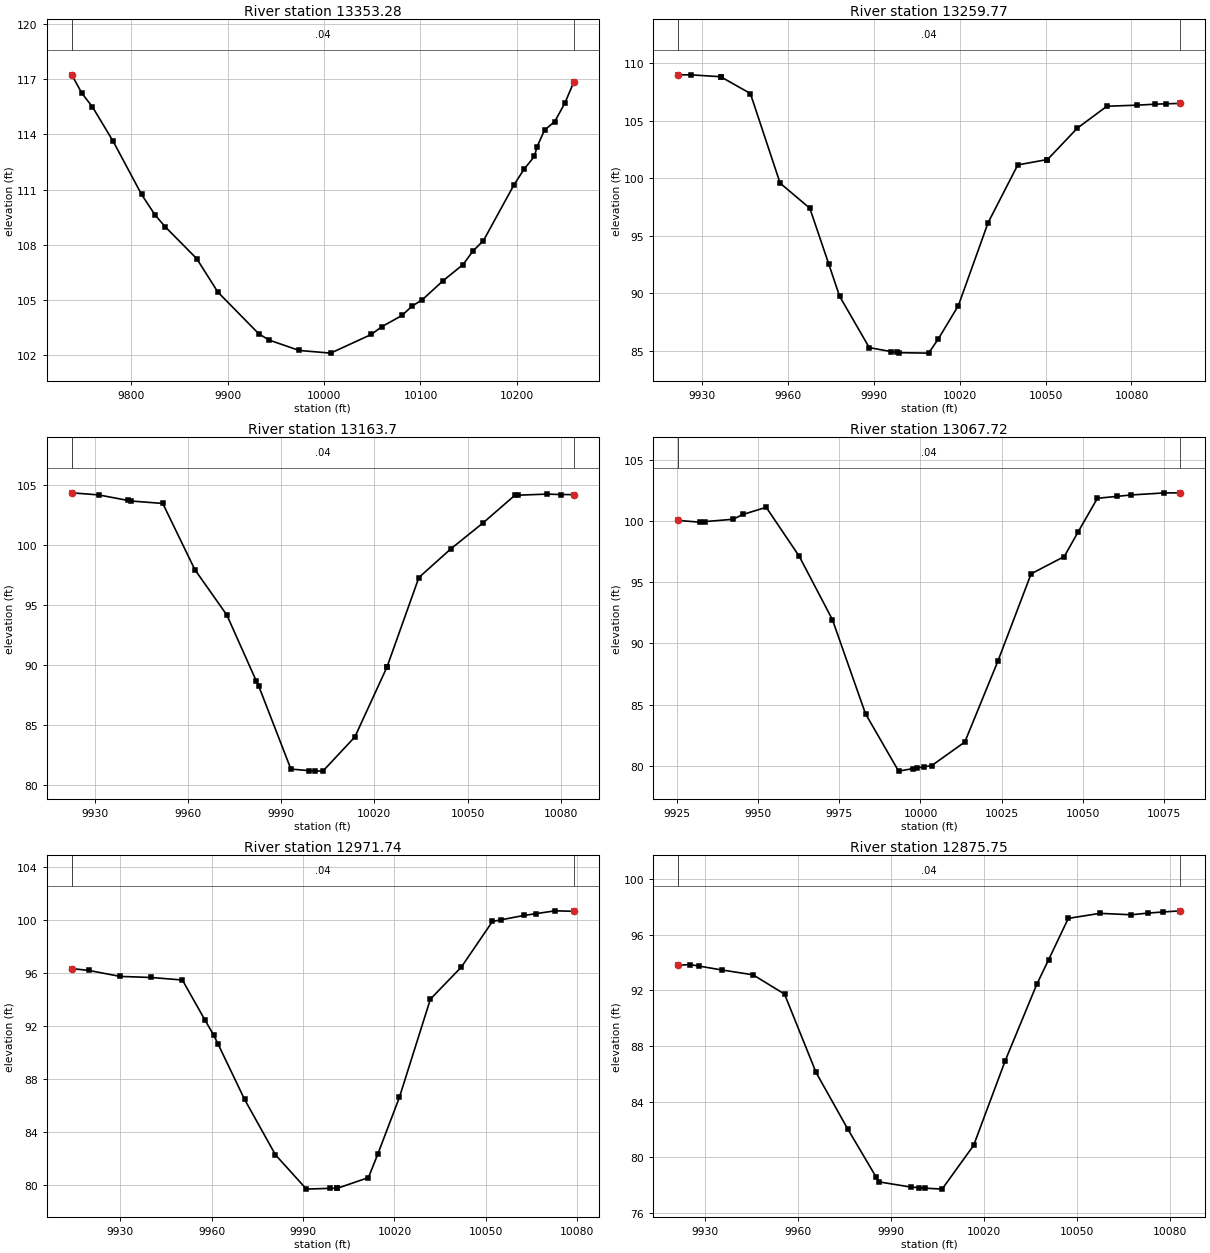
Type RM Length L Ch R = 1 ,13353.28,93.509200,93.509200,93.509200
XS GIS Cut Line= 6
 862585.31398602 849902.89972862862690.619832958849858.886441443
862756.600668355849832.555810555862798.405417122849817.075682247
862826.375800723849807.148574804863073.777806418849722.639591201
#Sta/Elev= 30
9738.242117.2385 9748.74116.23429759.578115.50559781.255113.61659810.591110.7411
9824.608109.62259835.447108.96239867.859107.24619889.842105.42619932.373103.1545
9943.037102.81879974.169102.256410006.79102.110410049.06103.127410059.63103.5399
10080.76104.156110091.33104.666810101.89105.011510123.03106.027610144.16106.9247
10154.73107.6785 10165.3108.2233   10197111.256910207.57112.115410218.13112.8005
10220.87113.3167 10228.7114.233810239.27114.696710249.84115.704810259.11 116.853
#Mann= 3 , 0 , 0
9738.242    0.04       09738.242    0.04       010259.11    0.04       0
#XS Ineff= 2 , 0
       09967.995        10001.69       0
Bank Sta=9738.242,10259.11
Exp/Cntr=0.3,0.1

Type RM Length L Ch R = 1 ,13259.77,96.076000,96.076000,96.076000
XS GIS Cut Line= 4
862760.721248652 849918.92361009862832.474461502849899.218703733
862834.422176732849898.764379921862929.712639672849872.705334717
#Sta/Elev= 26
9921.841109.00359926.278109.00319936.648 108.8379936.657108.83729947.018107.3761
9957.38999.575939967.75997.389869974.419 92.49569978.12989.739219988.49985.25749
9996.25184.907449998.25184.83649 9998.8584.8181410009.2284.7786110012.5285.98714
10019.5888.9067210029.95 96.123510040.32101.161510050.43101.620210050.69101.6261
10061.05  104.3510071.42106.270210081.79106.361210088.34106.446510092.15106.4825
10097.04106.5179
#Mann= 3 , 0 , 0
9921.841    0.04       09921.841    0.04       010097.04    0.04       0
#XS Ineff= 2 , 0
       0                               0
Bank Sta=9921.841,10097.04
Exp/Cntr=0.3,0.1

Type RM Length L Ch R = 1 , 13163.7,95.980900,95.980900,95.980900
XS GIS Cut Line= 5
862786.589112586850009.367007878862860.660282377849990.902328554
862862.611695662 849990.46416642862939.286017443849971.748108125
862943.414464535849970.658926964
#Sta/Elev= 24
9922.662104.3358 9931.33104.16219940.716103.70289941.636103.65719951.942103.4519
9962.24897.952329972.55494.170619982.05988.66283 9982.8688.228329993.16681.35154
    999981.22518   1000181.1996410003.4681.1828410013.7584.0289710024.0489.81928
10024.0589.8211410034.3497.2893110044.6399.6756610054.93  101.8210065.22104.1298
10066.21104.137810075.51104.230310079.93104.1933 10084.2104.1877
#Mann= 3 , 0 , 0
9922.662    0.04       09922.662    0.04       0 10084.2    0.04       0
#XS Ineff= 2 , 0
       0                               0
Bank Sta=9922.662,10084.2
Exp/Cntr=0.3,0.1

Type RM Length L Ch R = 1 ,13067.72,95.980900,95.980900,95.980900
XS GIS Cut Line= 6
862808.475648724850099.059471413862816.569127165850097.223058522
862880.632797038 850084.75588122862882.592847211850084.358133467
862940.765342824 850072.68955479862959.856918388850068.065884209
#Sta/Elev= 24
9925.435100.03319932.12599.895269933.73599.942549942.324100.13279945.372 100.528
9952.511101.10819962.69997.099639972.88691.937159983.07484.253159993.26279.56829
9997.72279.77648    999979.82987   1000179.9145510003.4680.0216910013.6581.94835
10023.8588.5671510034.0595.6792410044.2597.0888710048.5899.1309410054.45101.8452
10060.33101.997710064.69102.113910074.98102.282210079.97102.2905
#Mann= 3 , 0 , 0
9925.435    0.04       09925.435    0.04       010079.97    0.04       0
#XS Ineff= 2 , 0
       0                               0
Bank Sta=9925.435,10079.97
Exp/Cntr=0.3,0.1

Type RM Length L Ch R = 1 ,12971.74,95.980900,95.980900,95.980900
XS GIS Cut Line= 6
862819.503717773850193.986204417862866.468088121850184.113960405
862902.747639623850177.737706272862904.729292044850177.467421748
 862957.75732693850167.652660573862981.017923668850162.211374557
#Sta/Elev= 25
9914.17496.34247 9919.7996.201619930.00995.750969940.22795.669599950.44695.47958
9957.857 92.45369960.66491.339319962.16490.635859970.827 86.4706 9980.9882.27689
9991.13479.69014    999979.75243   1000179.7577910001.2879.7578810011.4580.55743
10014.5682.3525210021.6186.6178410031.7894.0373810041.95 96.462310052.1299.89871
10054.93100.022510062.37100.351310066.57100.494210072.64100.702910078.82100.6687
#Mann= 3 , 0 , 0
9914.174    0.04       09914.174    0.04       010078.82    0.04       0
#XS Ineff= 2 , 0
       0                               0
Bank Sta=9914.174,10078.82
Exp/Cntr=0.3,0.1

Type RM Length L Ch R = 1 ,12875.75,95.980900,95.980900,95.980900
XS GIS Cut Line= 5
 862841.25713904850286.150964722862917.627657886850272.578811854
862919.600587823 850272.25086759862990.190597612850259.167783115
863000.389219576850256.724150403
#Sta/Elev= 24
9921.43393.812729925.23493.866379928.01193.761459935.39193.478439945.54893.12744
9955.70491.735579965.86186.091979976.018 82.04139985.16378.582649986.174 78.2107
9996.33177.84169    999977.79228   1000177.7596210006.4977.6890810016.6680.84283
10026.8386.93502   1003792.4349810040.7994.1970810047.17 97.191410057.3497.55488
10067.5197.4512610072.7997.5727310077.74 97.653610083.2897.73612
#Mann= 3 , 0 , 0
9921.433    0.04       09921.433    0.04       010083.28    0.04       0
#XS Ineff= 2 , 0
       0                               0
Bank Sta=9921.433,10083.28
Exp/Cntr=0.3,0.1

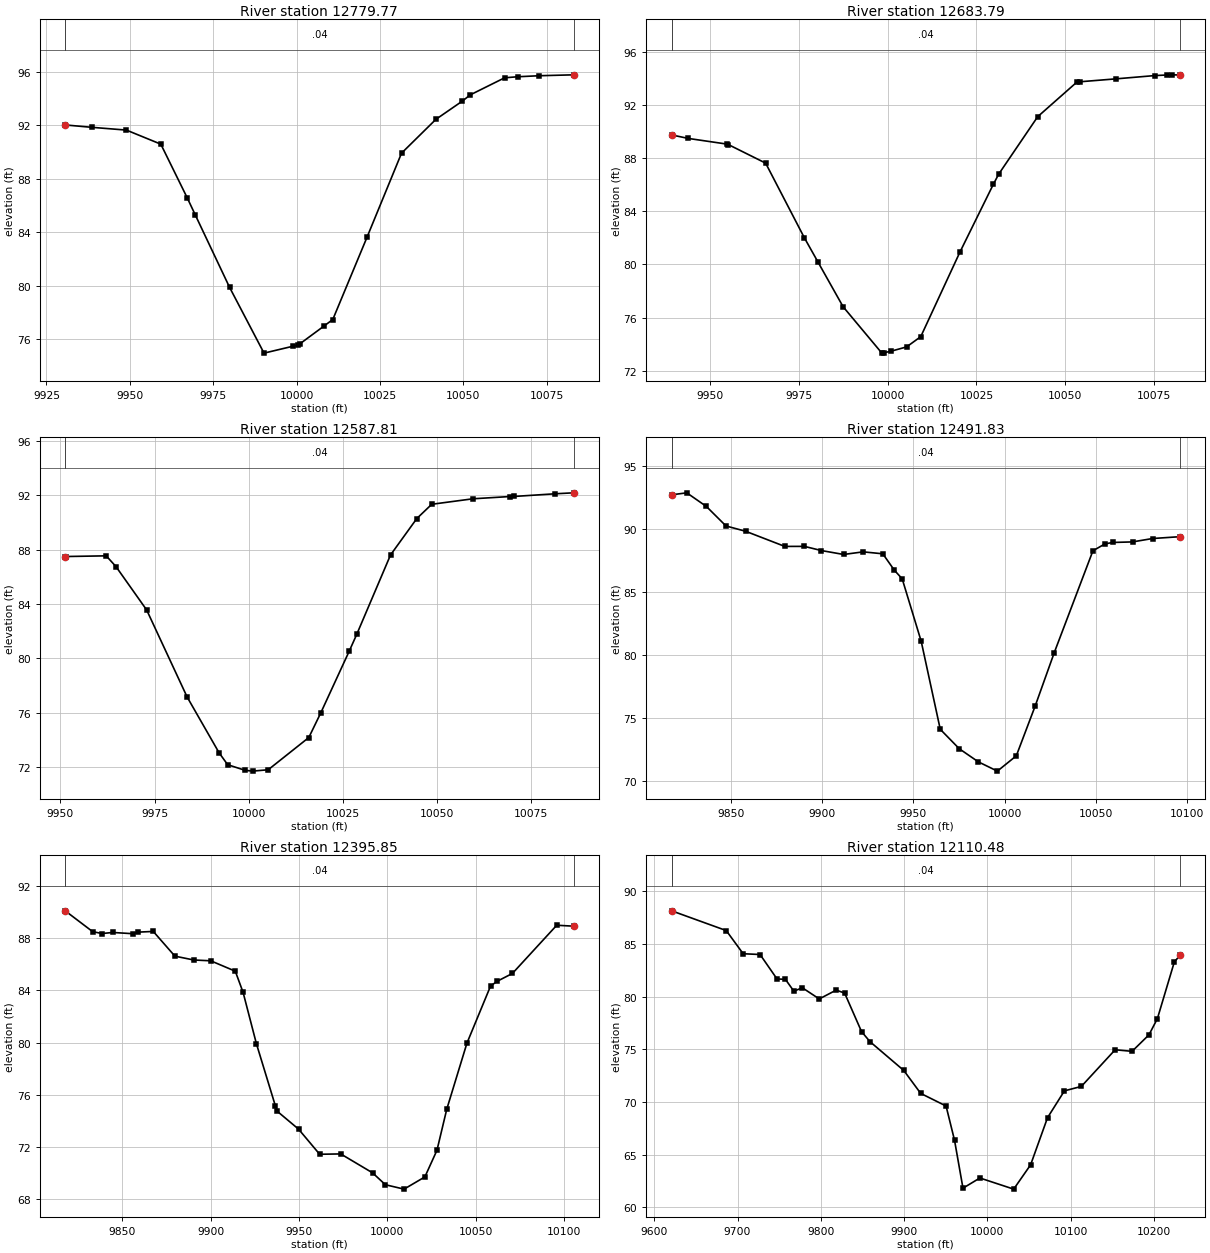
Type RM Length L Ch R = 1 ,12779.77,95.980900,95.980900,95.980900
XS GIS Cut Line= 5
862867.210037849850383.979669024862933.502321232850367.219003092
862935.435904685850366.707872005862998.783085554850351.000123745
863014.834533178850346.176576327
#Sta/Elev= 22
9930.62292.027289938.65791.848369948.97191.642089959.28690.590099967.25686.54794
9969.60185.306769979.91579.87171 9990.2374.95658    999975.4780210000.5575.57363
   1000175.65445 10008.1 76.962210010.85 77.470710021.1683.6558510031.4689.91504
10041.7692.4457110049.6593.8036410052.0794.2772810062.3795.5542910066.2795.63206
10072.7695.7088810083.0395.77656
#Mann= 3 , 0 , 0
9930.622    0.04       09930.622    0.04       010083.03    0.04       0
#XS Ineff= 2 , 0
       0                               0
Bank Sta=9930.622,10083.03
Exp/Cntr=0.3,0.1

Type RM Length L Ch R = 1 ,12683.79,95.980900,95.980900,95.980900
XS GIS Cut Line= 5
862910.750430052850481.361503124862965.544321138850457.584657296
862967.379665984850456.789981621863039.408727498850424.410335994
863041.541990907850423.535339419
#Sta/Elev= 24
 9939.2789.750289943.90289.487229954.80389.059459955.25189.017829965.70487.62585
9976.60582.001949980.37280.206519987.50676.810489998.40773.31953    999973.34972
   1000173.4650210005.37 73.788310009.3574.5617110020.3280.9009510029.76 86.0281
10031.2886.7995910042.2591.1241110053.2193.7132510054.1493.7522610064.1793.96928
10075.1494.2174810078.5394.2605110079.9794.2656510082.28 94.2747
#Mann= 3 , 0 , 0
 9939.27    0.04       0 9939.27    0.04       010082.28    0.04       0
#XS Ineff= 2 , 0
       0                               0
Bank Sta=9939.27,10082.28
Exp/Cntr=0.3,0.1

Type RM Length L Ch R = 1 ,12587.81,95.980900,95.980900,95.980900
XS GIS Cut Line= 5
862964.878411938850559.924748939863009.277594539 850542.48771156
 863011.14020748850541.759238488863036.826897526850531.446267763
863089.400673515850508.162937727
#Sta/Elev= 23
  9951.387.49182 9951.4387.492959962.17487.543289964.77286.752039972.91783.55886
9983.66177.150859992.12773.052759994.40472.17485    999971.76536   1000171.70206
10005.1671.8022210015.9474.1758510019.1476.0042610026.7180.5603910028.6881.78162
10037.6287.60753 10044.690.2897610048.5691.3373610059.4991.7411810069.2991.90723
10070.4391.9136710081.3792.1106410086.1892.17985
#Mann= 3 , 0 , 0
  9951.3    0.04       0  9951.3    0.04       010086.18    0.04       0
#XS Ineff= 2 , 0
       0                               0
Bank Sta=9951.3,10086.18
Exp/Cntr=0.3,0.1

Type RM Length L Ch R = 1 ,12491.83,95.980900,95.980900,95.980900
XS GIS Cut Line= 6
862867.288621523850694.743139167862980.905329944850650.472847892
863037.801832867850633.726974841863061.827973444850627.289392396
863091.165028018850617.101027799863128.724234946850600.315823595
#Sta/Elev= 27
9817.75392.741989826.02992.898939836.76291.814279847.49490.263649858.22689.84238
9879.69188.637439890.42388.640199899.677 88.30899911.88887.99698 9922.62 88.2044
9933.35388.04977 9939.6986.741219943.95986.061889954.383 81.08419964.80774.09204
9975.23172.544319985.65571.503529996.07970.7654110006.4571.98342 10016.875.95276
10027.2380.19183 10048.488.2915510054.9388.8322510059.1388.9518110070.0888.99545
10081.04 89.264610096.0789.41147
#Mann= 3 , 0 , 0
9817.753    0.04       09817.753    0.04       010096.07    0.04       0
#XS Ineff= 2 , 0
       0                               0
Bank Sta=9817.753,10096.07
Exp/Cntr=0.3,0.1

Type RM Length L Ch R = 1 ,12395.85,285.374000,285.374000,285.374000
XS GIS Cut Line= 6
862921.394755319850815.093494304862991.241689738850776.382775759
863076.186617246850721.027652105863077.668961699850719.685022229
863093.837609428850709.890736128863162.937813325850659.388409802
#Sta/Elev= 30
9817.75490.100819833.30988.502389838.57688.361659844.74288.441329856.17588.34611
9859.20588.468929867.60888.520269879.83486.627299890.474 86.33259900.14386.26914
9914.03285.472759918.459 83.84139925.968 79.92019936.77675.122969937.90474.71937
 9949.8473.364219961.776 71.43919973.71271.464199991.72470.01516    999969.10212
10009.5768.7657210021.3469.7016910028.1971.7466410033.7374.8922910045.1479.95211
 10058.584.3270710062.0984.6880910070.8985.2993810095.98 88.995610105.4988.92491
#Mann= 3 , 0 , 0
9817.754    0.04       09817.754    0.04       010105.49    0.04       0
#XS Ineff= 2 , 0
       0                               0
Bank Sta=9817.754,10105.49
Exp/Cntr=0.3,0.1

Type RM Length L Ch R = 1 ,12110.48,316.081500,316.081500,316.081500
XS GIS Cut Line= 2
862900.445669221850855.134489097863501.700115049850959.486318764
#Sta/Elev= 30
9620.96788.122429686.48686.250959706.78584.054369727.08483.981949747.383 81.6686
9757.533 81.62429767.68280.504539777.832 80.82919798.13179.76965 9818.4380.60545
9828.57980.328269848.87876.677479859.028 75.72199899.62672.989649919.92570.81585
9950.37369.619749960.52366.376699970.67261.830459990.971 62.796710031.5761.74145
10051.8764.0458110072.1768.5111610092.4771.0583710112.7671.4759510153.3674.95282
10173.6674.8028310193.9676.3672510204.11 77.913110224.4183.2786610231.21 83.8993
#Mann= 3 , 0 , 0
9620.967    0.04       09620.967    0.04       010231.21    0.04       0
#XS Ineff= 2 , 0
       09952.006        10056.41       0
Bank Sta=9620.967,10231.21
Exp/Cntr=0.3,0.1

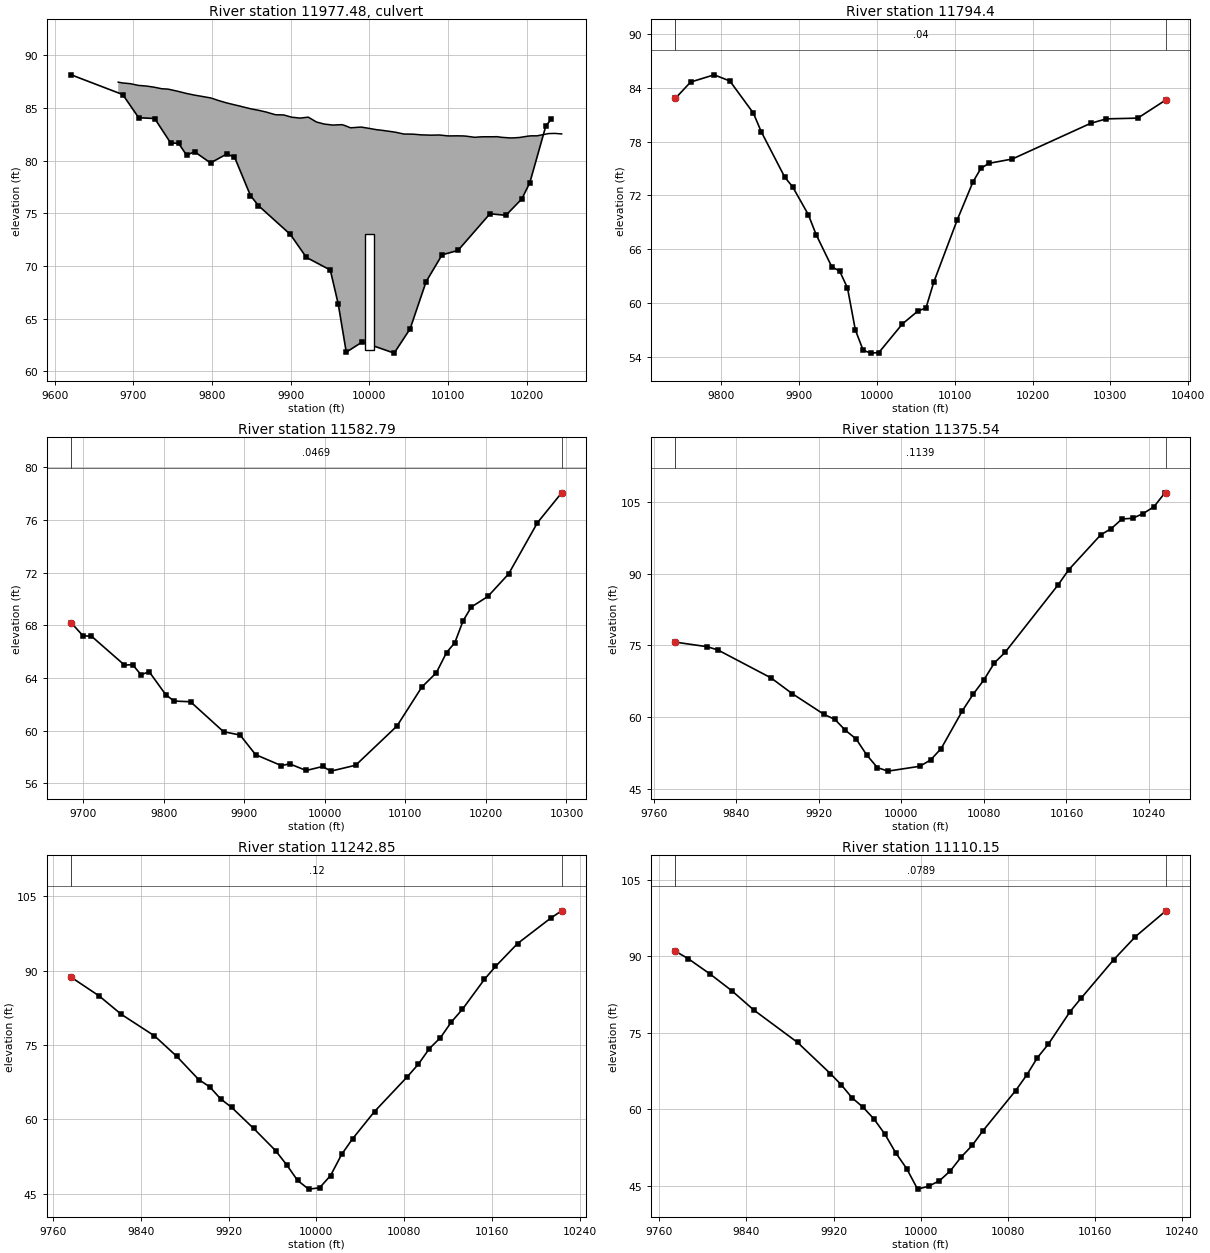
Type RM Length L Ch R = 2 ,11977.48,,,
Bridge Culvert--1,0,-1,-1, 0
Deck Dist Width WeirC Skew NumUp NumDn MinLoCord MaxHiCord MaxSubmerge Is_Ogee
25.541,265,2.6,0,76,76, , , 0.95, 0, 0,0,,
 9680.75 9686.38 9696.39 9706.40 9716.41 9726.41 9736.42 9741.78 9743.78 9746.50
 9756.64 9766.79 9776.94 9787.08 9796.10 9797.26 9800.17 9807.69 9818.11 9828.54
 9835.48 9838.97 9849.39 9859.82 9870.25 9870.80 9880.67 9891.10 9901.53 9906.11
 9911.95 9922.38 9932.81 9941.43 9943.23 9953.66 9954.05 9964.91 9967.94 9976.19
 9987.47 9989.56 9998.7510010.0310011.1810021.3010032.5810032.8010043.8610054.41
10055.1410066.4210076.0310077.7010088.9810097.6510100.2610111.5410119.2710122.82
10134.1010140.8810145.3810156.6610162.5010167.9410179.2210184.1210190.5010201.77
10205.7410213.0510224.3310227.3510235.6110244.50
   87.43   87.35   87.28   87.12   87.06   86.95   86.80   86.78   86.77   86.73
   86.56   86.37   86.21   86.08   85.96   85.95   85.89   85.70   85.47   85.28
   85.16   85.09   84.90   84.75   84.57   84.55   84.34   84.32   84.10   84.07
   84.02   84.11   83.65   83.48   83.45   83.36   83.36   83.40   83.34   83.10
   83.16   83.17   83.06   82.91   82.91   82.81   82.69   82.69   82.51   82.50
   82.50   82.43   82.41   82.40   82.42   82.35   82.33   82.34   82.33   82.31
   82.20   82.24   82.25   82.25   82.26   82.20   82.14   82.15   82.18   82.31
   82.34   82.34   82.50   82.55   82.57   82.52
                                                                                
                                                                                
                                                                                
                                                                                
                                                                                
                                                                                
                                                                                
                                                
 9680.75 9686.38 9696.39 9706.40 9716.41 9726.41 9736.42 9741.78 9743.78 9746.50
 9756.64 9766.79 9776.94 9787.08 9796.10 9797.26 9800.17 9807.69 9818.11 9828.54
 9835.48 9838.97 9849.39 9859.82 9870.25 9870.80 9880.67 9891.10 9901.53 9906.11
 9911.95 9922.38 9932.81 9941.43 9943.23 9953.66 9954.05 9964.91 9967.94 9976.19
 9987.47 9989.56 9998.7510010.0310011.1810021.3010032.5810032.8010043.8610054.41
10055.1410066.4210076.0310077.7010088.9810097.6510100.2610111.5410119.2710122.82
10134.1010140.8810145.3810156.6610162.5010167.9410179.2210184.1210190.5010201.77
10205.7410213.0510224.3310227.3510235.6110244.50
   87.43   87.35   87.28   87.12   87.06   86.95   86.80   86.78   86.77   86.73
   86.56   86.37   86.21   86.08   85.96   85.95   85.89   85.70   85.47   85.28
   85.16   85.09   84.90   84.75   84.57   84.55   84.34   84.32   84.10   84.07
   84.02   84.11   83.65   83.48   83.45   83.36   83.36   83.40   83.34   83.10
   83.16   83.17   83.06   82.91   82.91   82.81   82.69   82.69   82.51   82.50
   82.50   82.43   82.41   82.40   82.42   82.35   82.33   82.34   82.33   82.31
   82.20   82.24   82.25   82.25   82.26   82.20   82.14   82.15   82.18   82.31
   82.34   82.34   82.50   82.55   82.57   82.52
                                                                                
                                                                                
                                                                                
                                                                                
                                                                                
                                                                                
                                                                                
                                                
BR Coef=-1 , 0 , 0 ,, 0 ,,,0.8,-1,,0,
WSPro=,,,, 1 ,,,, 0 ,,,, 0 ,,,,-1 ,-1 ,-1 , 0 , 0 , 0 , 0 , 0
Culvert=2,11,11,265,0.013,0.5,1,8,3,62,10000,54,10000,Culvert #1, 0, 25.541
Culvert Bottom n=0.013
BC Design=,, 0 ,, 0 ,,,,,,

Type RM Length L Ch R = 1 , 11794.4,211.608900,211.608900,211.608900
XS GIS Cut Line= 2
862955.655672032851194.010279334863580.885661605851273.866664203
#Sta/Elev= 30
 9740.9982.861029760.49284.673879790.73585.483349810.89884.797759841.14281.20752
9851.22379.136269881.46774.051419891.54872.97702 9911.71 69.87379921.79167.63523
9941.954 64.02499952.03563.560779962.116 61.65899972.19856.979559982.27954.69508
 9992.3654.3870910002.4454.4539410032.6957.6520510052.85 59.110310062.9359.42616
10073.0162.3220710103.25 69.298710123.42 73.5289 10133.575.0220610143.5875.58959
10173.8276.0738610274.63 80.0662 10294.880.5624710335.12 80.6441 10371.3 82.6813
#Mann= 3 , 0 , 0
 9740.99    0.04       0 9740.99    0.04       0 10371.3    0.04       0
#XS Ineff= 2 , 0
       0                10041.62       0
Bank Sta=9740.99,10371.3
Exp/Cntr=0.3,0.1

Type RM Length L Ch R = 1 ,11582.79,207.245100,207.245100,207.245100
XS GIS Cut Line= 2
 862890.53734331851505.999295033863484.328464012851370.322707398
#Sta/Elev= 30
9684.92868.191289699.76467.195659710.02267.179989751.05364.98405 9761.3165.00659
9771.56864.250559781.82664.471029802.34162.732069812.59962.246729833.11462.19327
9874.14559.915889894.66159.66587 9913.8858.177889945.94957.339689956.20757.47631
9976.72256.970679997.23857.27455 10007.556.9226510038.2757.3723110089.56  60.353
10120.3363.3039410138.3564.39274 10151.165.9354810161.3666.6811910171.6268.34332
10181.8869.3934410202.3970.1932110228.1371.9039810263.9475.7951810294.0278.06684
#Mann= 3 , 0 , 0
9684.928  0.0469       09684.928  0.0469       010294.02  0.0469       0
#XS Ineff= 2 , 0
       09968.956                       0
Bank Sta=9684.928,10294.02
Exp/Cntr=0.3,0.1

Type RM Length L Ch R = 1 ,11375.54,132.695000,132.695000,132.695000
XS GIS Cut Line= 2
862905.152179442851573.214883543863366.270852065851687.756718545
#Sta/Elev= 30
9781.16175.689049811.91674.73882 9822.2274.064659873.73968.218969894.34764.91885
9925.25960.566739935.56359.543729945.86757.244359956.17155.461219966.475  52.097
9976.77849.458799987.08248.7191410017.9949.73803 10028.351.05082 10038.653.44665
10059.2161.3617810069.5164.7841410079.8267.7397910090.1271.3511910100.4373.53997
10151.9487.6877210162.2590.8565310193.1698.1330310203.4699.4472310213.77101.4514
10224.07101.597310234.38102.595710244.68103.997710254.98106.819910256.29106.9195
#Mann= 3 , 0 , 0
9781.161  0.1139       09781.161  0.1139       010256.29  0.1139       0
#XS Ineff= 2 , 0
       0                               0
Bank Sta=9781.161,10256.29
Exp/Cntr=0.3,0.1

Type RM Length L Ch R = 1 ,11242.85,132.694900,132.694900,132.694900
XS GIS Cut Line= 6
862879.735232876851737.467034002863030.120333883851755.591102385
863073.561966785851756.272103466863130.672892453851751.078641906
863168.242973498 851750.33921513863325.084472362851763.050845338
#Sta/Elev= 30
9776.37988.67312 9801.8884.905449822.066 81.20159852.346  76.8519872.50172.75794
9892.59568.051629902.64266.582219912.68964.141329922.73662.423489942.76258.18776
9962.76553.713249972.77150.879429982.80647.708979992.84145.9476210002.8946.21076
10012.9348.6925910022.9852.93604   1003356.1026510053.0161.6022510083.0468.64547
10093.0571.1664810103.0674.3031210113.0876.4748510123.1179.6692410133.1682.21623
10153.2488.2619110163.2990.8456110183.3895.4639610213.51100.575710223.64102.0724
#Mann= 3 , 0 , 0
9776.379    0.12       09776.379    0.12       010223.64    0.12       0
#XS Ineff= 2 , 0
       0                               0
Bank Sta=9776.379,10223.64
Exp/Cntr=0.3,0.1

Type RM Length L Ch R = 1 ,11110.15,132.695000,132.695000,132.695000
XS GIS Cut Line= 6
862853.541345465851862.506659982862952.097724377851873.963299761
 863076.80117082851882.068043276863088.428462798 851883.27263124
863221.703804901851881.357996412863302.914010611851882.036404758
#Sta/Elev= 30
9774.813  90.9689786.34989.545939806.48486.529129826.61983.229299846.75379.45687
9886.96373.097859917.02667.004159927.04764.802869937.06862.23304 9947.0960.40468
9957.11158.106119967.132 55.13549977.15351.457319987.174 48.36279997.19544.34996
10007.25 44.913710017.2745.9912210027.27 47.932210037.2750.6575310047.27 52.9027
10057.2755.8021910087.2763.6691810097.2866.6752510107.2870.1311210117.2872.77297
10137.28 79.163810147.2881.7561510177.2889.3168210197.2893.84809 10225.298.89544
#Mann= 3 , 0 , 0
9774.813  0.0789       09774.813  0.0789       0 10225.2  0.0789       0
#XS Ineff= 2 , 0
       0                               0
Bank Sta=9774.813,10225.2
Exp/Cntr=0.3,0.1