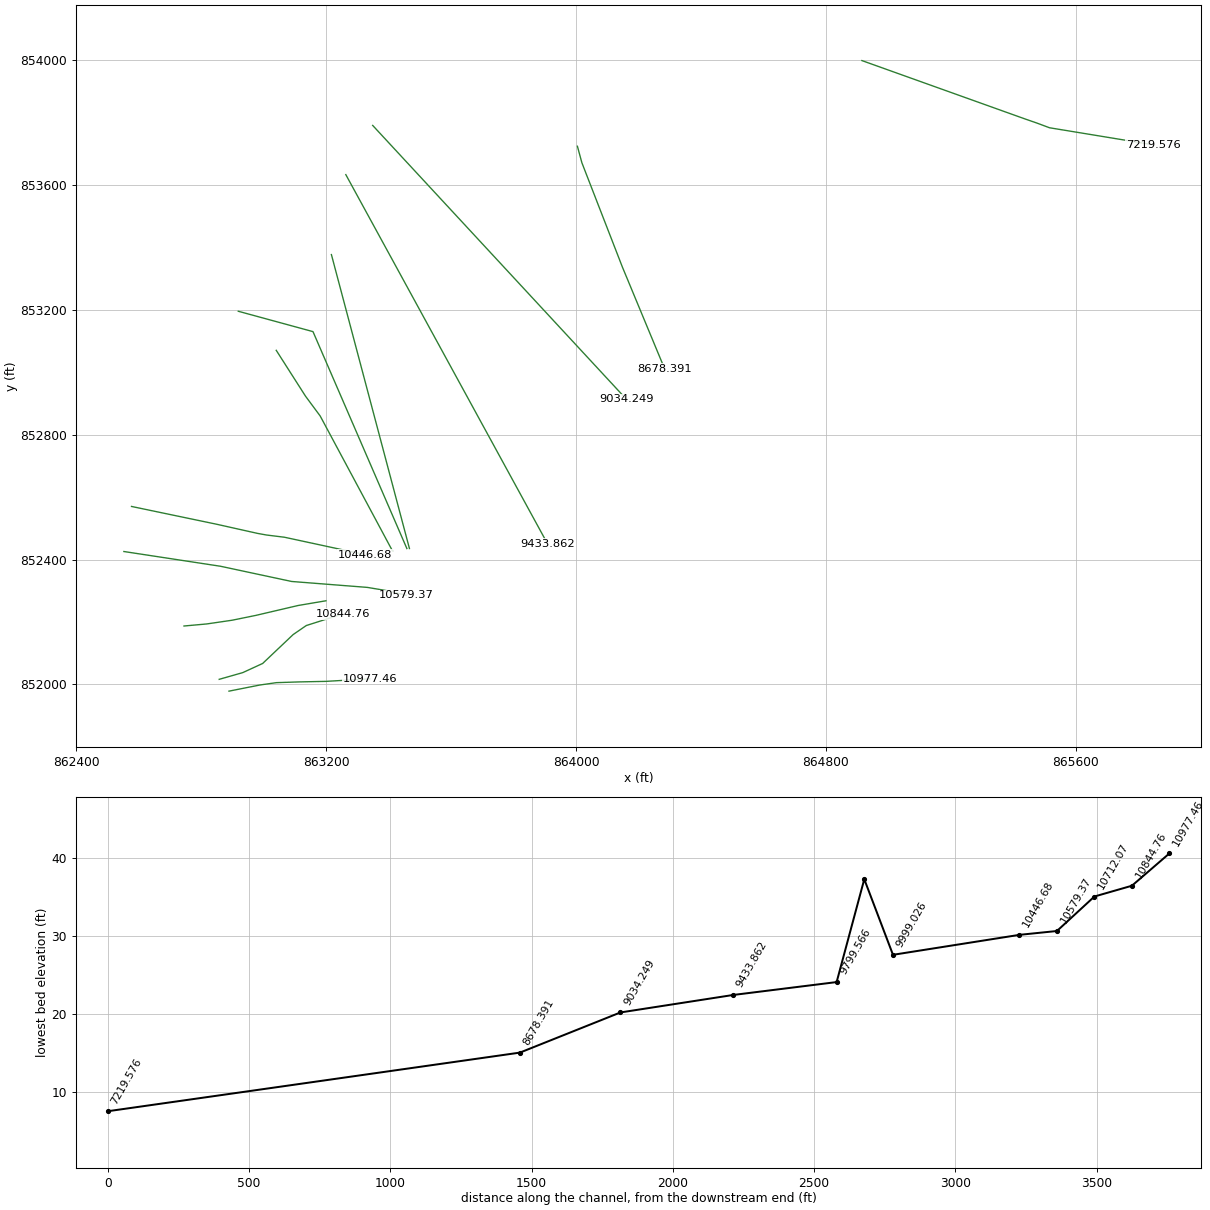
HEC-RAS study 16979_ras.prj: 16979

--- 16979_ras.g01 (geometry) --- (continued)

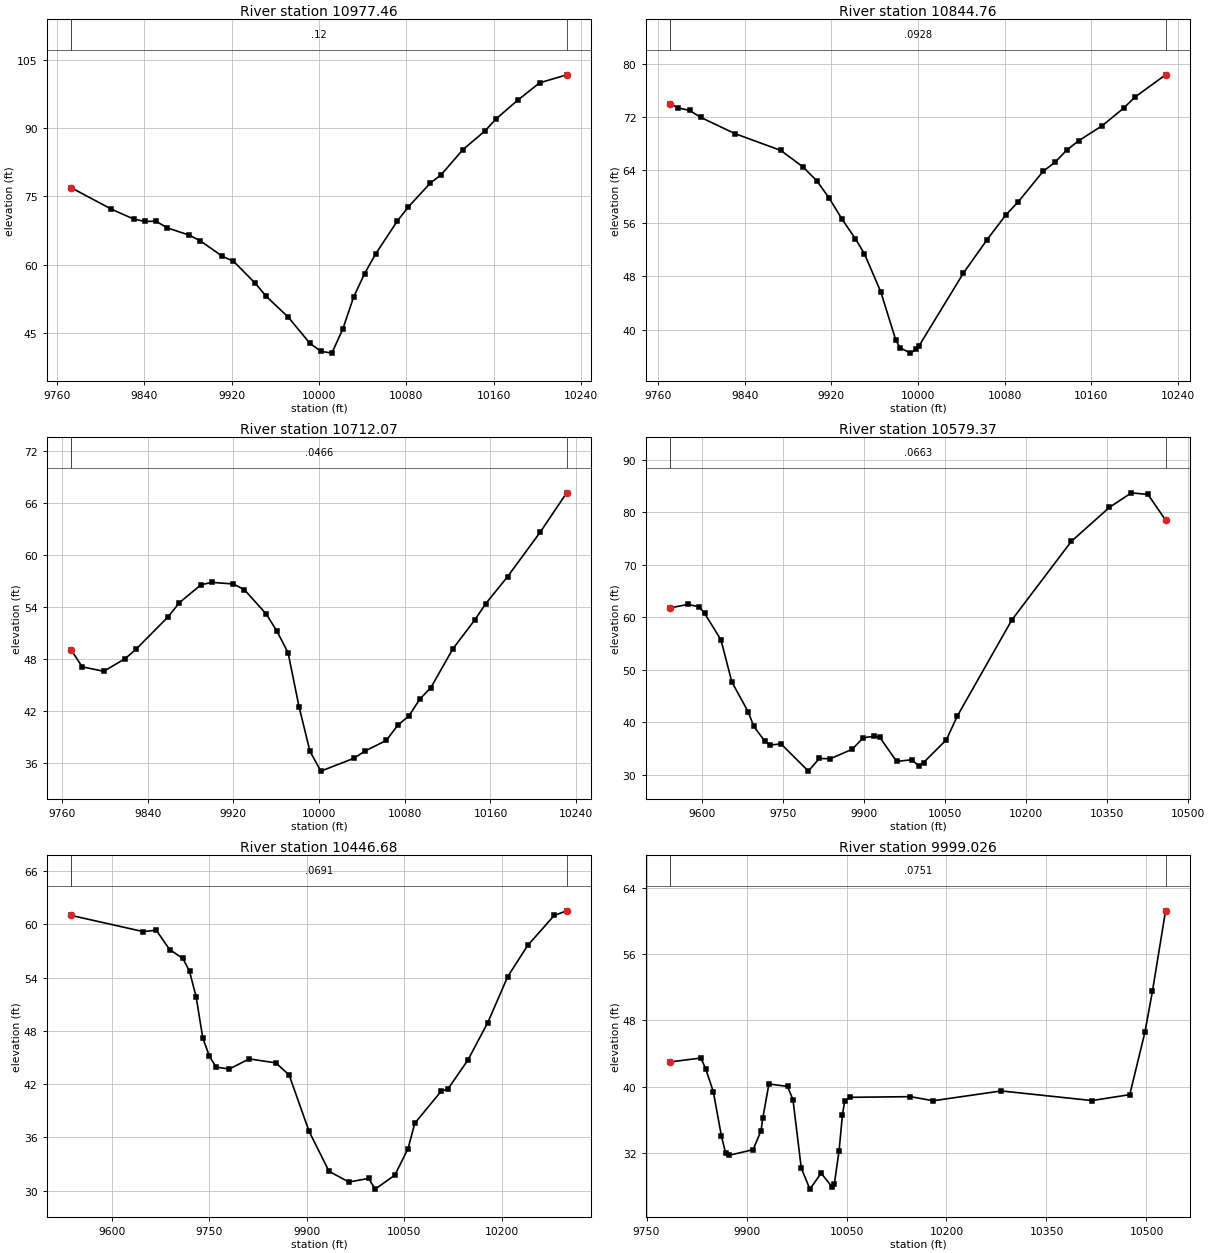
Type RM Length L Ch R = 1 ,10977.46,132.695000,132.695000,132.695000
XS GIS Cut Line= 6
862889.070749853851978.587799005862988.034872969851998.252004661
 863040.55058029852005.759118025863114.281713852852008.158462946
863199.048353254852009.880326129863339.784715195852017.979677176
#Sta/Elev= 30
9773.28176.888619809.91372.203399830.30470.03903  9840.569.513219850.69569.56694
9860.891 68.11649881.21666.496529891.31865.258679911.52161.846599921.62360.78457
9941.68755.918939951.69253.049949971.70348.533949991.71342.7327610001.7241.00204
10011.7240.5998710021.7245.8501610031.7252.9355510041.7358.0674910051.73 62.3356
10071.7369.6172710081.7372.6878510101.7677.8934210111.7879.7558610131.8185.29742
10151.8489.3579810161.8691.9764310181.8996.1215710201.9399.9338210226.75101.7034
#Mann= 3 , 0 , 0
9773.281    0.12       09773.281    0.12       010226.75    0.12       0
#XS Ineff= 2 , 0
       0                               0
Bank Sta=9773.281,10226.75
Exp/Cntr=0.3,0.1

Type RM Length L Ch R = 1 ,10844.76,132.695000,132.695000,132.695000
XS GIS Cut Line= 6
862857.814543429852016.436453785 862933.24001592852037.944480101
 862996.86800382852067.225554453863094.392297646   852159.652726
863136.482697394 852188.59517977 863252.65624594852225.591156157
#Sta/Elev= 30
9771.465 73.94639778.87973.374629789.19672.998319799.51471.953399830.81869.52169
 9873.3466.979239893.73164.512399906.66462.392039917.95459.820519929.95556.61355
9942.11853.703649950.48951.455079965.76745.636649979.40338.48413  9983.337.28132
 9993.0436.454549998.00937.00508   10001 37.552710041.92  48.50510063.6853.51048
10080.87 57.2194 10092.6 59.251710115.4763.82183 10126.565.1965810137.5267.05151
10148.24 68.423310170.2270.7158610189.9273.3612210200.1674.9986210228.5178.35816
#Mann= 3 , 0 , 0
9771.465  0.0928       09771.465  0.0928       010228.51  0.0928       0
#XS Ineff= 2 , 0
       0                               0
Bank Sta=9771.465,10228.51
Exp/Cntr=0.3,0.1

Type RM Length L Ch R = 1 ,10712.07,132.694900,132.694900,132.694900
XS GIS Cut Line= 6
862745.008585709852187.129419633862817.860544715852193.722076612
862899.276044806852205.658835724862974.326717475852220.960180191
863110.552150993852252.817392611863199.429568624852267.880805742
#Sta/Elev= 30
9768.94649.015819778.97847.11346 9799.0646.595449819.14148.062649829.18249.13673
9859.418 52.90999869.52554.498439889.73956.573859899.84656.863819920.05956.67357
9930.22856.028959950.65753.217779960.87151.190459971.08548.74805  9981.342.53132
9991.51437.3662410001.6935.07231 10032.536.5510810042.7737.3822810062.6638.60882
10073.5840.3800410083.85 41.442210094.12 43.399810104.3944.7177310124.9349.19668
10145.4352.5396310155.6154.4117510175.9857.5309110206.3862.6538710231.0767.19731
#Mann= 3 , 0 , 0
9768.946  0.0466       09768.946  0.0466       010231.07  0.0466       0
#XS Ineff= 2 , 0
       09946.645                       0
Bank Sta=9768.946,10231.07
Exp/Cntr=0.3,0.1

Type RM Length L Ch R = 1 ,10579.37,132.695000,132.695000,132.695000
XS GIS Cut Line= 6
 862552.52398726852425.582578686862861.749986772852378.425476408
863089.743957986852329.673269593863331.929713063852310.731804688
863400.243042771852299.287339882863456.533726042852285.406698753
#Sta/Elev= 30
9541.85661.793469574.70762.459369594.938 61.98089605.05460.765289635.401 55.7152
9655.63247.659349685.97941.943779696.09439.205089716.32636.412849726.44135.62645
9746.67335.838839797.25130.648989817.48233.068529837.71333.005029878.36134.82385
9898.75237.016399919.15437.298279929.45437.088359960.354 32.50569988.329 32.8072
10001.4131.6648410010.2632.2825810052.4136.6078710072.8141.1579510173.4959.45892
10283.6974.4703910354.2580.9652210394.8183.7359710425.6283.41924 10458.178.52296
#Mann= 3 , 0 , 0
9541.856  0.0663       09541.856  0.0663       0 10458.1  0.0663       0
#XS Ineff= 2 , 0
       09920.805                       0
Bank Sta=9541.856,10458.1
Exp/Cntr=0.3,0.1

Type RM Length L Ch R = 1 ,10446.68,447.649800,447.649800,447.649800
XS GIS Cut Line= 6
862577.013085992852569.845160422862850.116048588852512.776030633
862980.239197814 852483.66506007863009.303308729852478.416050298
863066.571845911852471.322290397863323.708653923852415.867332621
#Sta/Elev= 30
9537.43461.011969647.75459.197089668.18659.343689688.61857.17141 9709.0556.16659
9719.26654.729579729.48251.840779739.69847.204839749.91445.13985 9760.1343.91526
9780.56243.69961 9811.2144.840379852.18344.394929872.67743.031679903.41936.66964
 9934.1632.160919964.77630.956189995.09131.3640710005.1630.1559810035.4431.73072
10055.8834.7316610066.11 37.577610107.0341.2115110117.2641.4480910147.95 44.7091
10178.6448.9436310209.3254.1223910240.02  57.63110280.9461.0148410300.0761.53685
#Mann= 3 , 0 , 0
9537.434  0.0691       09537.434  0.0691       010300.07  0.0691       0
#XS Ineff= 2 , 0
       09877.539                       0
Bank Sta=9537.434,10300.07
Exp/Cntr=0.3,0.1

Type RM Length L Ch R = 1 ,9999.026,101.600200,101.600200,101.600200
XS GIS Cut Line= 4
863040.332276563853069.662275181863133.860325942 852923.12096249
863181.040486454852859.384608116 863412.36724725852427.650296988
#Sta/Elev= 30
9785.71742.983619831.56843.446799838.70142.159039850.15539.383149862.42733.97666
9868.74331.92485 9874.2931.69419 9909.8832.366599921.74334.650759924.50536.23511
9933.60640.312879961.47740.016189969.66538.422249982.10730.133829995.09227.59593
 10011.929.5249710028.7127.8305610031.8728.2682410038.8632.2574310043.8336.56029
10047.2438.2282810055.1838.6980310145.9438.7785810179.9738.2828810282.0839.47101
10418.2238.3054610474.94 39.022410497.6346.5596310508.9851.5390910528.6661.25138
#Mann= 3 , 0 , 0
9785.717  0.0751       09785.717  0.0751       010528.66  0.0751       0
#XS Ineff= 2 , 0
       09946.415        10062.94       0
Bank Sta=9785.717,10528.66
Exp/Cntr=0.3,0.1

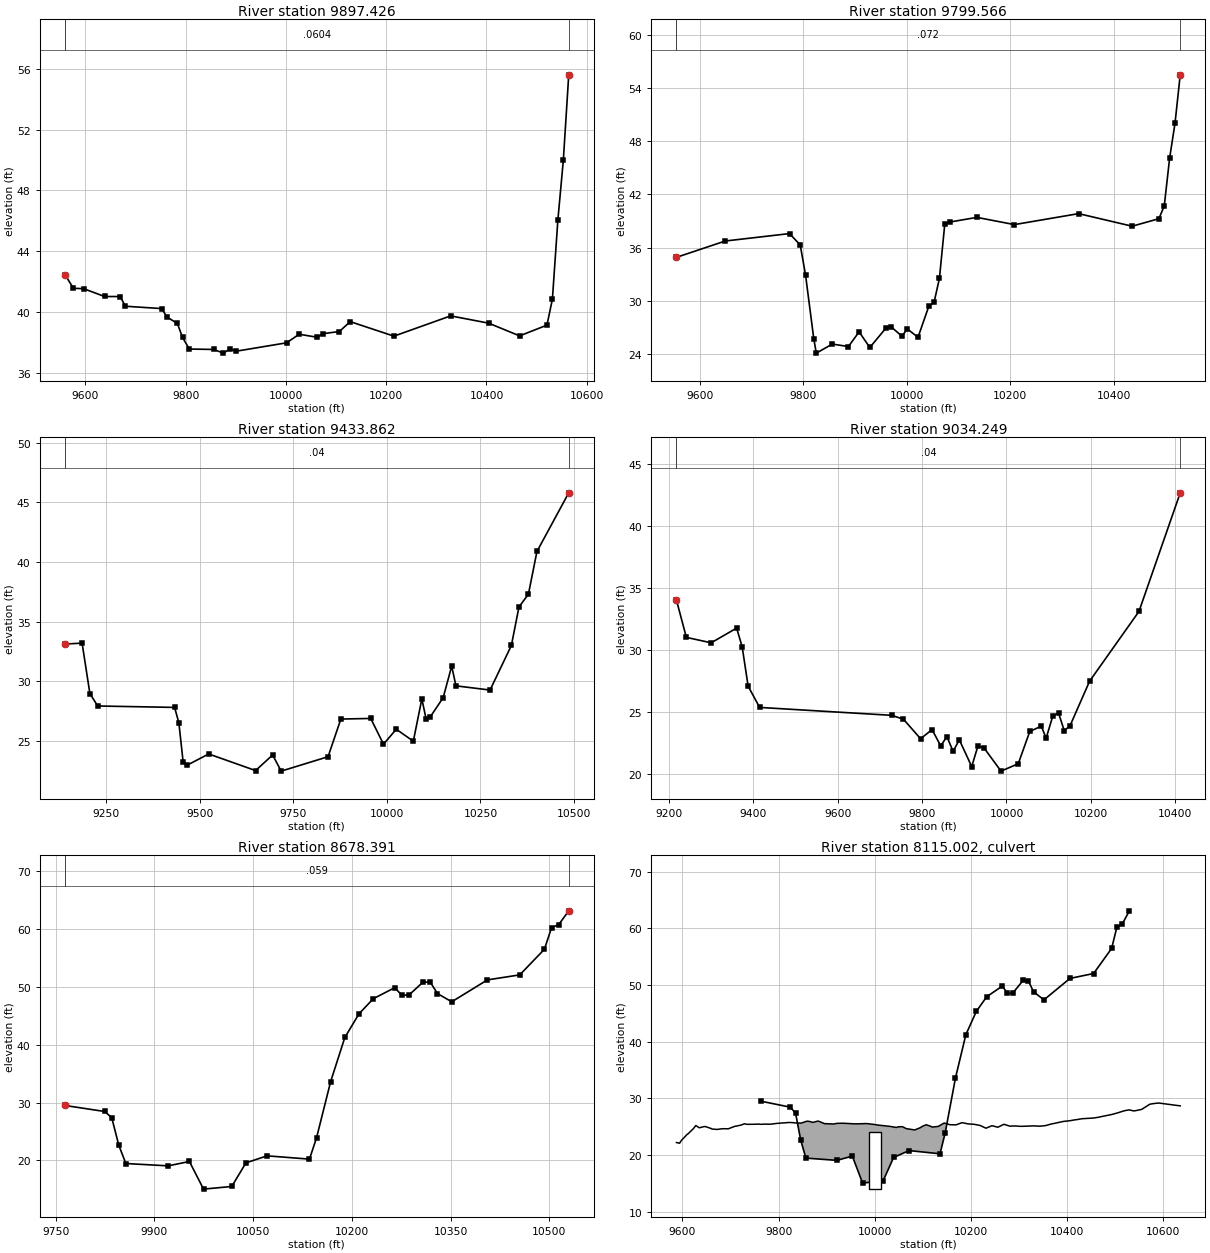
Type RM Length L Ch R = 1 ,9897.426,97.860400,97.860400,97.860400
XS GIS Cut Line= 3
862918.792571306853194.750949308863157.965234816853129.543299213
 863458.52947098 852435.09885478
#Sta/Elev= 30
9559.43942.458279576.23841.55421 9596.5141.532369638.428 41.01649669.52341.01242
9679.88840.375589752.44340.220869762.80839.666229783.53839.241879793.90338.32006
9807.34237.558979855.87837.532049875.40437.289919888.56737.57632 9900.5837.41507
10001.2837.9677410026.4638.5325610062.9138.3314310073.8138.57004 10106.538.71005
10128.2939.3614710215.46 38.407710328.5739.74123 10404.139.2637410466.0838.42534
10520.5639.1318110531.4640.8428110542.3546.0474810553.2549.9828310564.0455.60357
#Mann= 3 , 0 , 0
9559.439  0.0604       09559.439  0.0604       010564.04  0.0604       0
#XS Ineff= 2 , 0
       09961.529        10079.77       0
Bank Sta=9559.439,10564.04
Exp/Cntr=0.3,0.1

Type RM Length L Ch R = 1 ,9799.566,365.703600,365.703600,365.703600
XS GIS Cut Line= 2
863216.920700457853376.171966779863466.732051851852435.199774333
#Sta/Elev= 30
9554.81534.898829649.14536.738769773.30237.575159793.99536.294539804.34132.87866
9820.13425.742449825.03424.099359856.07325.120939887.11224.840449907.80526.49812
9928.49824.735369959.537 26.91649969.88427.050769990.576 26.008910000.9226.82935
10021.6225.8815710042.3129.3564410052.6529.82538   1006332.5246610073.3538.64343
10083.6938.8826710135.4339.4021610207.8538.5880710332.0139.8243610435.4738.40671
 10487.239.2538110497.5540.70389 10507.946.0915310518.24 49.995310528.3855.47257
#Mann= 3 , 0 , 0
9554.815   0.072       09554.815   0.072       010528.38   0.072       0
#XS Ineff= 2 , 0
       09921.459         10041.5       0
Bank Sta=9554.815,10528.38
Exp/Cntr=0.3,0.1

Type RM Length L Ch R = 1 ,9433.862,399.613400,399.613400,399.613400
XS GIS Cut Line= 2
863263.057805195853632.126427768863908.802502453852450.433063396
#Sta/Elev= 30
9139.48433.113859185.24133.194199206.09528.953349226.94927.915619432.49727.79705
9443.89226.506799455.28823.232039466.68422.957049523.66223.889219649.01522.49508
9694.59723.805029717.38922.448229842.74123.658369876.928 26.8191 9956.83 26.8709
9990.88524.7071210025.0725.9621910070.6524.9595410093.4528.5116510104.8426.82124
10116.24 27.014910150.4228.6139310173.2231.2598510184.61 29.606610275.7829.25442
10332.7632.9977510353.05 36.225610378.34 37.304910401.1340.88787 10486.145.80906
#Mann= 3 , 0 , 0
9139.484    0.04       09139.484    0.04       0 10486.1    0.04       0
#XS Ineff= 2 , 0
       09882.196        10041.34       0
Bank Sta=9139.484,10486.1
Exp/Cntr=0.3,0.1

Type RM Length L Ch R = 1 ,9034.249,355.857500,355.857500,355.857500
XS GIS Cut Line= 2
863349.070719994853789.673166308864161.103725226852913.235741562
#Sta/Elev= 30
 9217.3233.997689240.75830.996879299.61330.558089360.01531.746079373.18130.23183
 9387.2827.057749414.54525.344859728.09124.705549755.73624.389919796.25322.81891
9823.51823.553749844.01822.242999858.732  22.9889873.44521.796989888.15922.73395
9917.58620.56767  9932.322.230049947.01322.062839987.10720.20347   1002820.80255
10055.2723.4019310082.5323.8341110094.15 22.8646 10109.824.6436110123.4324.89659
10137.0623.46698 10150.723.8597610197.1527.4599710314.2933.0930410412.1242.66156
#Mann= 3 , 0 , 0
 9217.32    0.04       0 9217.32    0.04       010412.12    0.04       0
#XS Ineff= 2 , 0
       09831.081        10116.96       0
Bank Sta=9217.32,10412.12
Exp/Cntr=0.3,0.1

Type RM Length L Ch R = 1 ,8678.391,1458.815700,1458.815700,1458.815700
XS GIS Cut Line= 4
864004.420604081853723.011261356864018.835384739853670.000234657
 864148.48314039853336.233213755 864283.54370584  853010.8373129
#Sta/Elev= 30
9764.24329.495649824.54328.455049835.27127.397229845.99922.625889856.72719.47263
9921.09419.071869953.278 19.82819974.73415.0534410017.6515.51423 10039.119.58324
10071.29 20.800110135.6520.2335510146.3823.8948510167.8433.62074 10189.441.23726
10211.06 45.339210232.7147.9335610265.1949.8267210276.0248.5290210286.8548.56971
 10308.550.8195410319.3350.7588210330.1648.8125610351.8147.3940710405.9551.17434
 10455.152.0401210492.5756.4598610503.3960.1812810514.2260.7056210529.5563.09837
#Mann= 3 , 0 , 0
9764.243   0.059       09764.243   0.059       010529.55   0.059       0
#XS Ineff= 2 , 0
       09949.577        10066.29       0
Bank Sta=9764.243,10529.55
Exp/Cntr=0.3,0.1

Type RM Length L Ch R = 2 ,8115.002,,,
Bridge Culvert--1,0,-1,-1, 0
Deck Dist Width WeirC Skew NumUp NumDn MinLoCord MaxHiCord MaxSubmerge Is_Ogee
4.408,1450,2.6,0,148,148, , , 0.95, 0, 0,0,,
 9587.56 9594.11 9597.75 9610.17 9610.97 9622.59 9627.83 9635.01 9644.69 9647.43
 9659.85 9661.55 9672.27 9678.41 9684.69 9695.27 9697.11 9709.53 9712.13 9721.95
 9728.99 9734.37 9745.85 9746.79 9759.22 9762.71 9771.64 9779.57 9784.06 9796.43
 9796.48 9808.90 9813.29 9821.32 9830.15 9833.74 9846.16 9847.01 9858.58 9863.87
 9871.00 9880.73 9883.42 9895.84 9897.59 9908.26 9914.45 9920.68 9931.31 9933.10
 9945.52 9948.17 9957.94 9965.03 9970.36 9981.89 9982.78 9995.21 9998.7510007.63
10015.6110020.0510032.4710032.4710044.8910049.3310057.3110066.2010069.7310082.15
10083.0610094.5710099.9210106.9910116.7810119.4110131.8310133.6410144.2510150.50
10156.6710167.3610169.0910181.5110184.2210193.9310201.0810206.3510217.9410218.77
10231.2010234.8010243.6210251.6610256.0410268.4610268.5210280.8810285.3810293.30
10302.2410305.7210318.1410319.1010330.5610335.9610342.9810352.8210355.4010367.82
10369.6810380.2410386.5410392.6610403.4010405.0810417.5010420.2610429.9210437.12
10442.3410453.9810454.7610467.1810470.8410479.6110487.7010492.0310504.4510504.56
10516.8710521.4210529.2910538.2810541.7110554.1310555.1410566.5510572.0010578.97
10588.8610591.3910603.8110605.7210616.2310622.5810628.6510635.25
   22.22   22.10   22.59   23.69   23.70   24.66   25.22   24.82   25.03   25.04
   24.69   24.60   24.53   24.61   24.66   24.64   24.70   25.10   25.12   25.30
   25.53   25.43   25.43   25.44   25.47   25.43   25.47   25.45   25.46   25.60
   25.60   25.66   25.70   25.76   25.73   25.68   25.65   25.65   25.98   25.95
   25.77   25.99   25.98   25.54   25.55   25.52   25.49   25.60   25.61   25.63
   25.57   25.56   25.52   25.52   25.54   25.57   25.57   25.45   25.41   25.29
   25.23   25.18   25.06   25.06   24.88   25.00   25.02   24.65   24.62   24.44
   24.44   24.84   25.12   25.36   25.07   24.95   25.06   25.14   25.66   25.52
   25.36   25.35   25.34   25.73   25.68   25.51   25.46   25.44   25.25   25.24
   24.75   24.87   25.19   25.02   24.92   25.44   25.44   25.11   25.13   25.14
   25.08   25.08   25.11   25.12   25.16   25.14   25.10   25.19   25.21   25.51
   25.53   25.72   25.85   25.95   26.04   26.06   26.24   26.26   26.41   26.46
   26.48   26.53   26.54   26.71   26.79   26.95   27.08   27.15   27.43   27.44
   27.77   27.87   27.98   27.80   27.83   28.06   28.07   28.69   28.98   29.08
   29.18   29.18   29.04   29.01   28.91   28.83   28.76   28.69
                                                                                
                                                                                
                                                                                
                                                                                
                                                                                
                                                                                
                                                                                
                                                                                
                                                                                
                                                                                
                                                                                
                                                                                
                                                                                
                                                                                
                                                                
 9587.56 9594.11 9597.75 9610.17 9610.97 9622.59 9627.83 9635.01 9644.69 9647.43
 9659.85 9661.55 9672.27 9678.41 9684.69 9695.27 9697.11 9709.53 9712.13 9721.95
 9728.99 9734.37 9745.85 9746.79 9759.22 9762.71 9771.64 9779.57 9784.06 9796.43
 9796.48 9808.90 9813.29 9821.32 9830.15 9833.74 9846.16 9847.01 9858.58 9863.87
 9871.00 9880.73 9883.42 9895.84 9897.59 9908.26 9914.45 9920.68 9931.31 9933.10
 9945.52 9948.17 9957.94 9965.03 9970.36 9981.89 9982.78 9995.21 9998.7510007.63
10015.6110020.0510032.4710032.4710044.8910049.3310057.3110066.2010069.7310082.15
10083.0610094.5710099.9210106.9910116.7810119.4110131.8310133.6410144.2510150.50
10156.6710167.3610169.0910181.5110184.2210193.9310201.0810206.3510217.9410218.77
10231.2010234.8010243.6210251.6610256.0410268.4610268.5210280.8810285.3810293.30
10302.2410305.7210318.1410319.1010330.5610335.9610342.9810352.8210355.4010367.82
10369.6810380.2410386.5410392.6610403.4010405.0810417.5010420.2610429.9210437.12
10442.3410453.9810454.7610467.1810470.8410479.6110487.7010492.0310504.4510504.56
10516.8710521.4210529.2910538.2810541.7110554.1310555.1410566.5510572.0010578.97
10588.8610591.3910603.8110605.7210616.2310622.5810628.6510635.25
   22.22   22.10   22.59   23.69   23.70   24.66   25.22   24.82   25.03   25.04
   24.69   24.60   24.53   24.61   24.66   24.64   24.70   25.10   25.12   25.30
   25.53   25.43   25.43   25.44   25.47   25.43   25.47   25.45   25.46   25.60
   25.60   25.66   25.70   25.76   25.73   25.68   25.65   25.65   25.98   25.95
   25.77   25.99   25.98   25.54   25.55   25.52   25.49   25.60   25.61   25.63
   25.57   25.56   25.52   25.52   25.54   25.57   25.57   25.45   25.41   25.29
   25.23   25.18   25.06   25.06   24.88   25.00   25.02   24.65   24.62   24.44
   24.44   24.84   25.12   25.36   25.07   24.95   25.06   25.14   25.66   25.52
   25.36   25.35   25.34   25.73   25.68   25.51   25.46   25.44   25.25   25.24
   24.75   24.87   25.19   25.02   24.92   25.44   25.44   25.11   25.13   25.14
   25.08   25.08   25.11   25.12   25.16   25.14   25.10   25.19   25.21   25.51
   25.53   25.72   25.85   25.95   26.04   26.06   26.24   26.26   26.41   26.46
   26.48   26.53   26.54   26.71   26.79   26.95   27.08   27.15   27.43   27.44
   27.77   27.87   27.98   27.80   27.83   28.06   28.07   28.69   28.98   29.08
   29.18   29.18   29.04   29.01   28.91   28.83   28.76   28.69
                                                                                
                                                                                
                                                                                
                                                                                
                                                                                
                                                                                
                                                                                
                                                                                
                                                                                
                                                                                
                                                                                
                                                                                
                                                                                
                                                                                
                                                                
BR Coef=-1 , 0 , 0 ,, 0 ,,,0.8,-1,,0,
WSPro=,,,, 1 ,,,, 0 ,,,, 0 ,,,,-1 ,-1 ,-1 , 0 , 0 , 0 , 0 , 0
Culvert=2,10,26,1450,0.013,0.4,1,8,1,14,10000,8,10000,Culvert #1, 0, 4.408
Culvert Bottom n=0.013
BC Design=,, 0 ,, 0 ,,,,,,

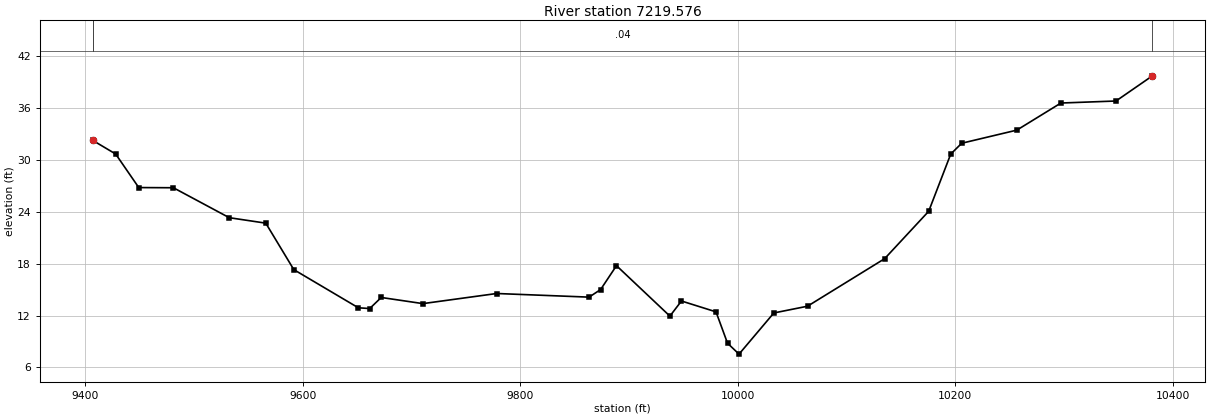
Type RM Length L Ch R = 1 ,7219.576,300.933000,300.933000,300.933000
XS GIS Cut Line= 6
864915.167758682853997.301782234865438.118106365853810.171320155
865472.932815932853798.127149588865474.824490669853797.477867939
 865515.79366976853782.204936697865848.073036226853727.618156675
#Sta/Elev= 30
9406.73832.243589427.80130.669659449.04326.792579480.906  26.7719532.29423.30952
9565.874 22.67859591.65617.305949651.01812.894059661.46212.806169672.08314.08584
 9710.3813.375469778.29314.54466 9863.2614.124689873.88115.003599888.46717.76361
9937.60711.930489948.22813.678369980.02412.423099990.6068.79823310001.197.535842
 10033.212.2947510064.1913.0749710135.1318.5703510175.6624.0517210195.9330.66608
10206.0631.9178610256.7333.4335710297.2736.5656210347.9436.7994610381.4639.71069
#Mann= 3 , 0 , 0
9406.738    0.04       09406.738    0.04       010381.46    0.04       0
#XS Ineff= 2 , 0
       09922.778        10060.86       0
Bank Sta=9406.738,10381.46
Exp/Cntr=0.3,0.1