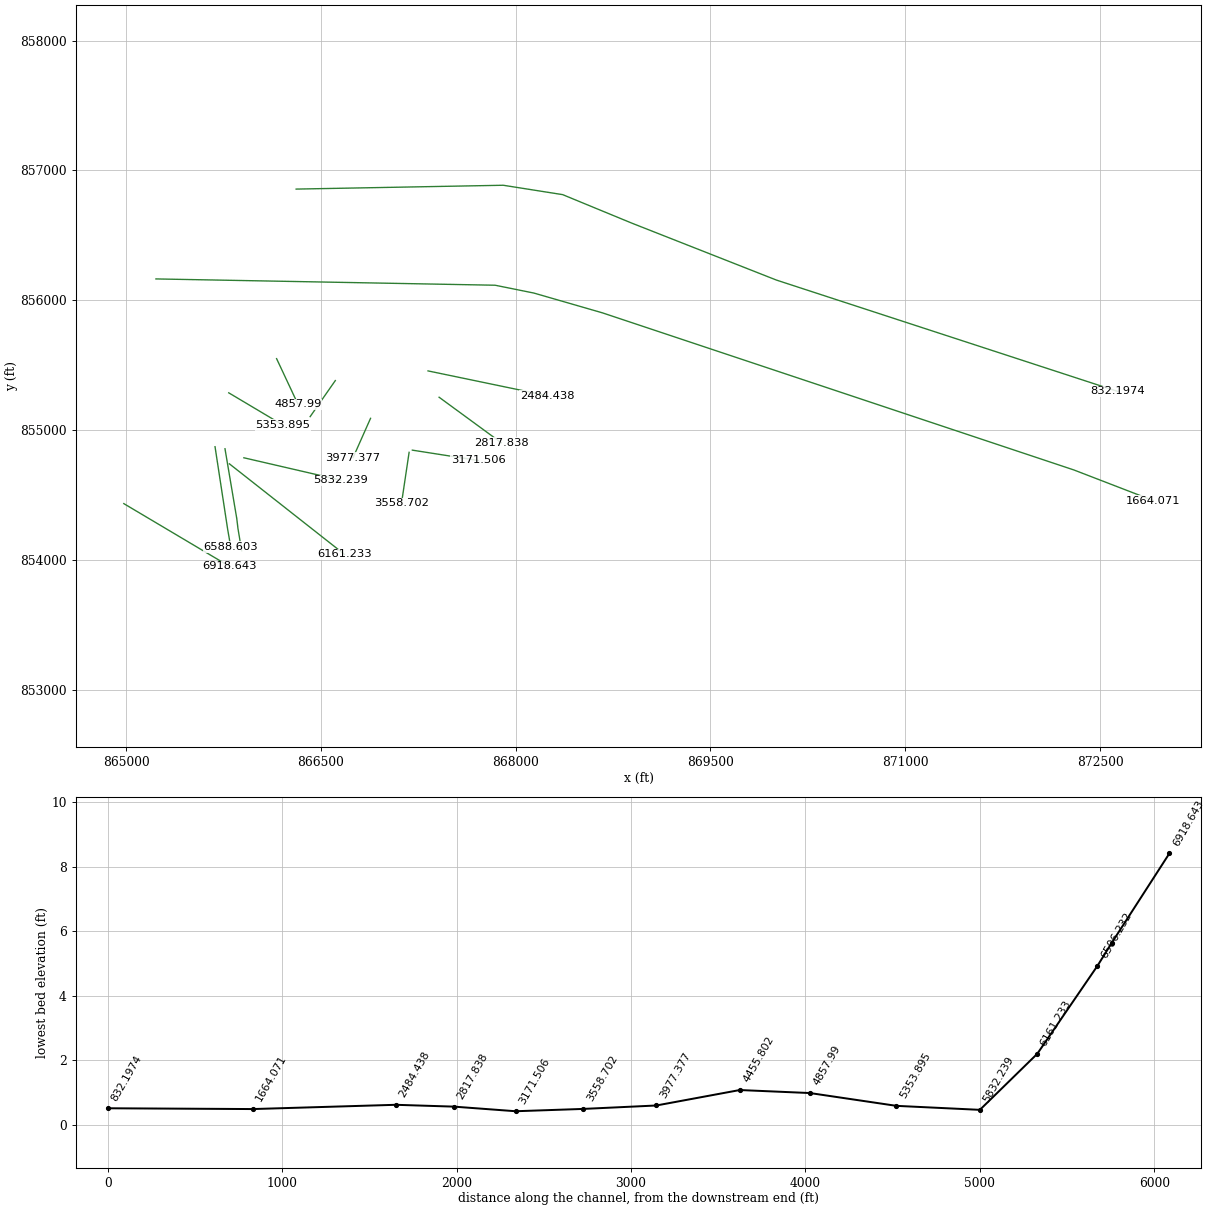
HEC-RAS study 16979_ras.prj: 16979

--- 16979_ras.g01 (geometry) --- (continued)

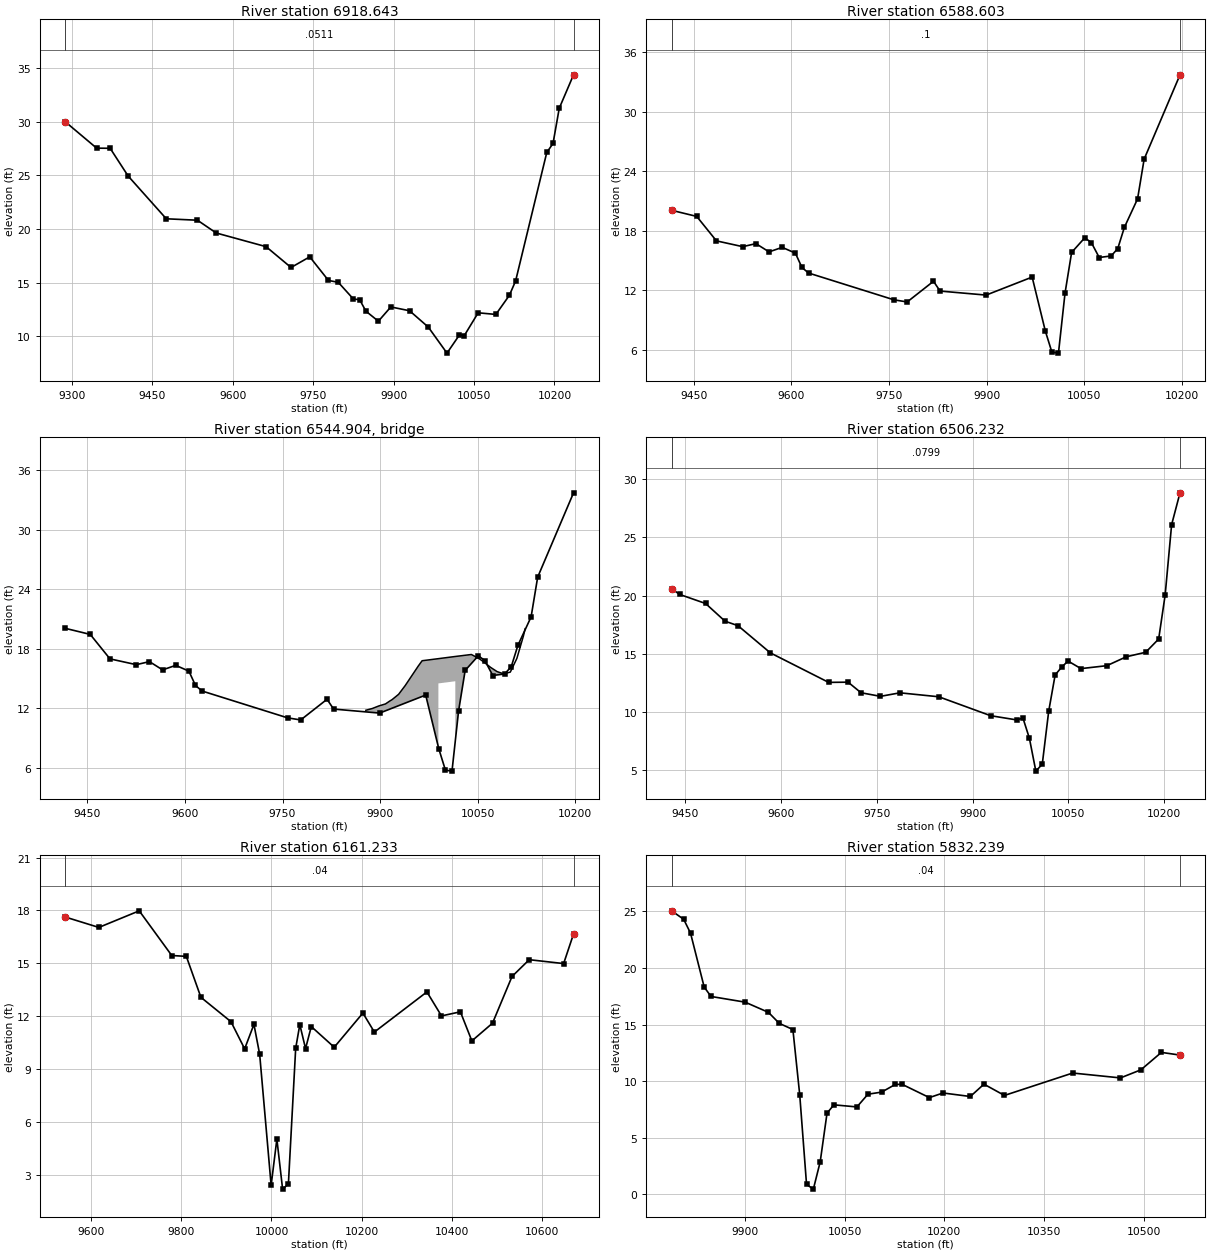
Type RM Length L Ch R = 1 ,6918.643,330.040000,330.040000,330.040000
XS GIS Cut Line= 2
864982.949658638854434.917695161865797.891288049853951.064808874
#Sta/Elev= 30
9287.88329.990549346.48527.524969371.67627.512459405.24824.923919476.343 20.9404
9534.49220.806349569.38119.617029662.41918.341059708.93816.400979743.82817.39341
9778.71715.190839797.00215.019669825.23613.458089836.86613.401149848.49612.33015
9871.75511.392099895.015 12.72379929.90412.367469964.79310.847669999.6828.417485
10022.9410.1136610032.0510.0587510057.8312.1770510090.8212.0249710115.9813.80317
10127.6115.1422110185.7627.1259410197.3927.9606310209.0231.2477110235.6434.36025
#Mann= 3 , 0 , 0
9287.883  0.0511       09287.883  0.0511       010235.64  0.0511       0
#XS Ineff= 2 , 0
       09836.774                       0
Bank Sta=9287.883,10235.64
Exp/Cntr=0.3,0.1

Type RM Length L Ch R = 1 ,6588.603,82.370600,82.370600,82.370600
XS GIS Cut Line= 4
865685.289376144 854873.06541182 865782.56747103854236.958415158
865795.375612589854163.897072763865804.855795371854100.448964118
#Sta/Elev= 30
9415.74820.061769454.25619.446929484.60516.97742 9525.0716.393539545.302 16.6998
9565.535 15.86729585.76716.32368    960615.740239616.11614.291969626.23213.73385
9757.744  11.0269777.97610.813079818.44112.899879828.55711.912149899.37111.50551
9970.18513.323889990.4187.88381910000.535.74817610010.655.64783910020.7711.71676
10030.8815.8084910051.1217.2900710061.24 16.803810073.3415.29949 10091.715.45675
10101.8516.20055   1011218.3377610132.3121.2133910142.4225.2252510197.5833.73668
#Mann= 3 , 0 , 0
9415.748     0.1       09415.748     0.1       010197.58     0.1       0
#XS Ineff= 2 , 0
       09849.435        10037.82       0
Bank Sta=9415.748,10197.58
Exp/Cntr=0.3,0.1

Type RM Length L Ch R = 3 ,6544.904,,,
BEGIN DESCRIPTION:
END DESCRIPTION:
Bridge Culvert--1,0,-1,-1, 0
Deck Dist Width WeirC Skew NumUp NumDn MinLoCord MaxHiCord MaxSubmerge Is_Ogee
26.685300,29.000000,2.6,0, 26, 26, , , 0.95, 0, 0,0,,
 9878.10 9888.10 9898.20 9908.31 9914.87 9918.41 9928.52 9938.62 9948.73 9958.83
 9964.68 9989.74 9989.7410015.7410015.7410040.4110049.7810053.9210059.8810069.99
10080.0910090.2010100.3010110.4110120.5110123.17
   11.79   11.97   12.23   12.43   12.72   12.86   13.40   14.28   15.27   16.26
   16.79   17.00   17.00   17.22   17.22   17.42   17.10   16.93   16.65   16.12
   15.69   15.47   15.64   17.02   19.29   20.02
 -988.21 -988.03 -987.77 -987.57 -987.28 -987.14 -986.60 -985.72 -984.73 -983.74
 -983.21 -983.00   14.50   14.72 -982.78 -982.58 -982.90 -983.07 -983.35 -983.88
 -984.31 -984.53 -984.36 -982.98 -980.71 -979.98
 9878.10 9888.10 9898.20 9908.31 9914.87 9918.41 9928.52 9938.62 9948.73 9958.83
 9964.68 9990.28 9990.2810016.2810016.2810040.4110049.7810053.9210059.8810069.99
10080.0910090.2010100.3010110.4110120.5110123.17
   11.79   11.97   12.23   12.43   12.72   12.86   13.40   14.28   15.27   16.26
   16.79   17.00   17.00   17.22   17.22   17.42   17.10   16.93   16.65   16.12
   15.69   15.47   15.64   17.02   19.29   20.02
 -988.21 -988.03 -987.77 -987.57 -987.28 -987.14 -986.60 -985.72 -984.73 -983.74
 -983.21 -983.00   14.50   14.72 -982.78 -982.58 -982.90 -983.07 -983.35 -983.88
 -984.31 -984.53 -984.36 -982.98 -980.71 -979.98
BR Coef=-1 , 0 , 0 ,, 0 ,,,0.8,0,1,0,
WSPro=,,,, 1 ,,,, 0 ,,,, 0 ,,,,-1 ,-1 ,-1 , 0 , 0 , 0 , 0 , 0
BC Design=,, 0 ,, 0 ,,,,,,

Type RM Length L Ch R = 1 ,6506.232,344.999300,344.999300,344.999300
XS GIS Cut Line= 4
865761.978021403854857.346484411865852.751904355854319.508453091
865861.651958684854244.591362745865890.445904287854072.063496691
#Sta/Elev= 30
9428.97720.593979441.499  20.1069482.06419.328389512.48917.807499532.77117.42458
9583.47915.087079674.75112.553139705.17612.570979725.45811.662179755.88311.35445
9786.307 11.65689847.15611.317619928.2879.6922999968.853 9.331629978.9629.483545
9989.0327.7466699999.1034.93138810009.17 5.5294510019.2410.0847910029.3113.19217
10039.38 13.852610049.4514.3865810069.7313.7356410110.2813.98792 10140.714.75262
10171.1115.1398710191.3916.2774210201.5320.0589710211.6626.0957110224.7828.83261
#Mann= 3 , 0 , 0
9428.977  0.0799       09428.977  0.0799       010224.78  0.0799       0
#XS Ineff= 2 , 0
       09830.449        10042.42       0
Bank Sta=9428.977,10224.78
Exp/Cntr=0.3,0.1

Type RM Length L Ch R = 1 ,6161.233,328.993700,328.993700,328.993700
XS GIS Cut Line= 2
865795.941780702854741.149163436866682.258728305854043.875072295
#Sta/Elev= 30
9542.39117.627949617.02917.03747  9706.617.978379778.762 15.44579811.10815.39682
9843.455 13.07639910.17811.693629940.49410.155639961.07311.543129973.7979.846472
9999.2442.42130510011.97 5.0409610024.692.20459210037.532.49706710053.7110.18887
10062.8611.5307610075.5910.1679910088.3111.41909 10139.210.2462410202.8212.18463
10228.2711.1068510344.8313.3821910377.1712.0227610419.1212.2545610444.5710.60552
10490.3811.6109810533.6414.2567610571.8115.2086310648.1514.9886610670.1116.66621
#Mann= 3 , 0 , 0
9542.391    0.04       09542.391    0.04       010670.11    0.04       0
#XS Ineff= 2 , 0
       09935.608        10066.86       0
Bank Sta=9542.391,10670.11
Exp/Cntr=0.3,0.1

Type RM Length L Ch R = 1 ,5832.239,478.344000,478.344000,478.344000
XS GIS Cut Line= 2
865907.353773241854787.799308502866652.264024628854615.472492175
#Sta/Elev= 30
9789.92225.035049808.03424.283629818.29823.063279838.82618.30385 9849.0917.47534
9900.41116.973019935.44616.073339951.731 15.10399972.25914.553799982.5248.801336
9992.7880.88028310003.050.46720910013.322.87878110023.58 7.1688710033.847.908596
10068.55  7.723910085.168.84752610105.699.03137610126.229.70835310136.499.720064
10177.548.54642410198.078.95488910239.138.64483410259.659.73342810290.458.738294
10393.0910.7162910464.9410.2847710495.7311.0001510526.5212.5382910554.5112.30055
#Mann= 3 , 0 , 0
9789.922    0.04       09789.922    0.04       010554.51    0.04       0
#XS Ineff= 2 , 0
       0                10227.93       0
Bank Sta=9789.922,10554.51
Exp/Cntr=0.3,0.1

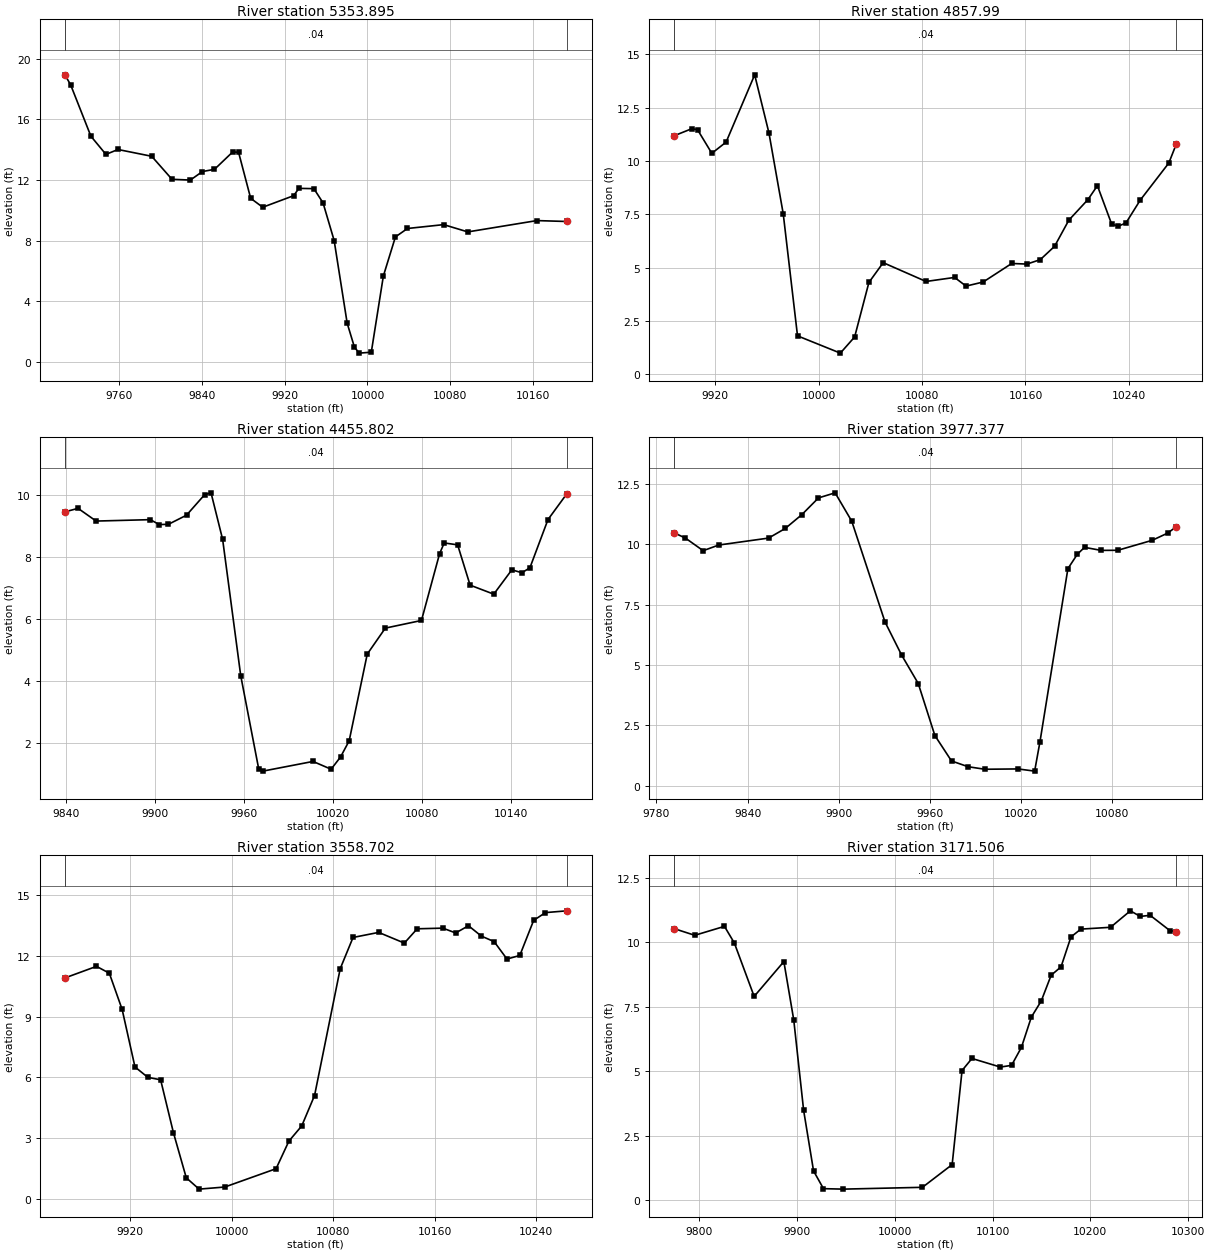
Type RM Length L Ch R = 1 ,5353.895,495.905300,495.905300,495.905300
XS GIS Cut Line= 2
865790.977857928855287.833166169866207.116137208855040.209424107
#Sta/Elev= 30
9708.10718.945879713.647 18.28749733.20314.897139747.69713.698869759.33314.02111
9791.86913.573679811.42512.055549829.15312.005159840.78912.566649852.42612.71309
9870.09113.865689875.69913.827599887.33510.801819898.97210.212569928.75810.97486
9933.88111.457369948.31311.438499957.15410.500529967.8698.0160449980.4272.563983
9987.4240.9845719992.0640.591047 10003.70.65211910015.345.67913210026.978.256128
10038.618.81166610073.529.06593210096.798.58617710163.429.33253710192.359.272356
#Mann= 3 , 0 , 0
9708.107    0.04       09708.107    0.04       010192.35    0.04       0
#XS Ineff= 2 , 0
       0                10150.31       0
Bank Sta=9708.107,10192.35
Exp/Cntr=0.3,0.1

Type RM Length L Ch R = 1 , 4857.99,402.187600,402.187600,402.187600
XS GIS Cut Line= 2
866159.279377089855551.153595701866324.086260311 855199.64318111
#Sta/Elev= 30
9888.537 11.18719902.013 11.51429906.37811.464079917.42310.357489928.46710.88449
9950.556 14.03849961.60111.311499972.645  7.5215 9983.691.79800310016.820.987981
10027.871.74687110038.914.30352310049.96 5.2296310083.094.34830810105.184.537777
10114.024.13128210127.27 4.3226310149.365.19192810161.13 5.1642510171.455.371834
10182.495.99584510193.54 7.2233110208.258.18407110215.638.83973810226.677.034986
 10231.86.94154610237.717.09209910248.768.16309110270.859.90180510276.7610.80935
#Mann= 3 , 0 , 0
9888.537    0.04       09888.537    0.04       010276.76    0.04       0
#XS Ineff= 2 , 0
       0                 10195.9       0
Bank Sta=9888.537,10276.76
Exp/Cntr=0.3,0.1

Type RM Length L Ch R = 1 ,4455.802,478.424900,478.424900,478.424900
XS GIS Cut Line= 2
866611.414345975855382.283680244 866417.65491503855104.563630611
#Sta/Elev= 30
9838.939  9.4506 9847.829.5648879860.0139.1541769896.5939.199704 9902.589.040995
9908.7869.049223 9920.989.3435769933.17310.003889937.53410.065679945.3668.559298
 9957.564.1640259969.7531.1371479972.4881.08133710006.331.39405610018.531.142943
10024.921.53939410030.722.06030610042.914.85913510055.115.69826810079.495.945091
10091.69 8.0976510094.838.44758210103.888.386563 10112.37.08545310128.276.794263
10140.467.57987810147.267.48578310152.657.64592510164.849.20243910177.5710.03561
#Mann= 3 , 0 , 0
9838.939    0.04       09838.939    0.04       010177.57    0.04       0
#XS Ineff= 2 , 0
       0                10081.24       0
Bank Sta=9838.939,10177.57
Exp/Cntr=0.3,0.1

Type RM Length L Ch R = 1 ,3977.377,418.675200,418.675200,418.675200
XS GIS Cut Line= 2
866882.665771438855091.592624142  866748.5230954854789.726488361
#Sta/Elev= 28
9791.87810.463629799.09210.251869810.7559.7305789820.9789.9643749853.80710.25242
9864.74910.649789875.69211.222999886.635 11.91589897.57812.126479908.52110.95357
9930.4076.780484 9941.355.4074639952.2934.2306449963.2362.0760419974.1791.023408
9985.121 0.784399996.064 0.6797710017.950.69300210028.890.60212510032.381.812054
10050.788.98619310057.019.58458210061.729.86875910072.66 9.7428310083.619.747315
10106.26 10.160210116.4410.4583710122.2110.72746
#Mann= 3 , 0 , 0
9791.878    0.04       09791.878    0.04       010122.21    0.04       0
#XS Ineff= 2 , 0
       0                               0
Bank Sta=9791.878,10122.21
Exp/Cntr=0.3,0.1

Type RM Length L Ch R = 1 ,3558.702,387.196100,387.196100,387.196100
XS GIS Cut Line= 2
867179.578060883854829.629661085867121.134511959854438.323357443
#Sta/Elev= 30
 9868.5810.904929893.48311.476369903.59411.139639913.7059.3531269923.8166.518557
9933.9276.0069149944.0375.8846749954.1483.2738029964.2591.054145 9974.370.495946
9994.5920.59957410035.041.50269810045.15 2.8634210055.263.61097910065.37 5.11086
10085.5911.36079 10095.712.9008410115.9213.1502210136.1412.6234910146.2613.32754
10166.4813.3603310176.5913.12274 10186.7 13.478810196.8112.9688110206.9212.69533
10217.0311.8380110227.1412.0126710238.0613.7427210247.3714.1259610264.2314.21349
#Mann= 3 , 0 , 0
 9868.58    0.04       0 9868.58    0.04       010264.23    0.04       0
#XS Ineff= 2 , 0
       0                               0
Bank Sta=9868.58,10264.23
Exp/Cntr=0.3,0.1

Type RM Length L Ch R = 1 ,3171.506,353.667700,353.667700,353.667700
XS GIS Cut Line= 2
867204.516884355854846.547300512867711.573179692854767.145820651
#Sta/Elev= 30
9774.758 10.51519795.49110.260929825.85710.607349835.9789.9616469856.222 7.89181
9886.5889.242375 9896.716.9787629906.8323.4712929916.9531.1293459927.0750.442239
9947.3190.42407910028.290.49441110058.661.37515110068.785.020073 10078.95.487943
10107.955.15456610119.395.22029510129.515.92032710139.637.09049610149.76 7.71668
10159.888.713121   101709.03971310180.1210.1965310190.2410.5004810220.6110.57106
10240.8511.2093110250.97 10.9926 10261.111.0356610281.3410.4414810287.9910.39619
#Mann= 3 , 0 , 0
9774.758    0.04       09774.758    0.04       010287.99    0.04       0
#XS Ineff= 2 , 0
       0                10077.14       0
Bank Sta=9774.758,10287.99
Exp/Cntr=0.3,0.1

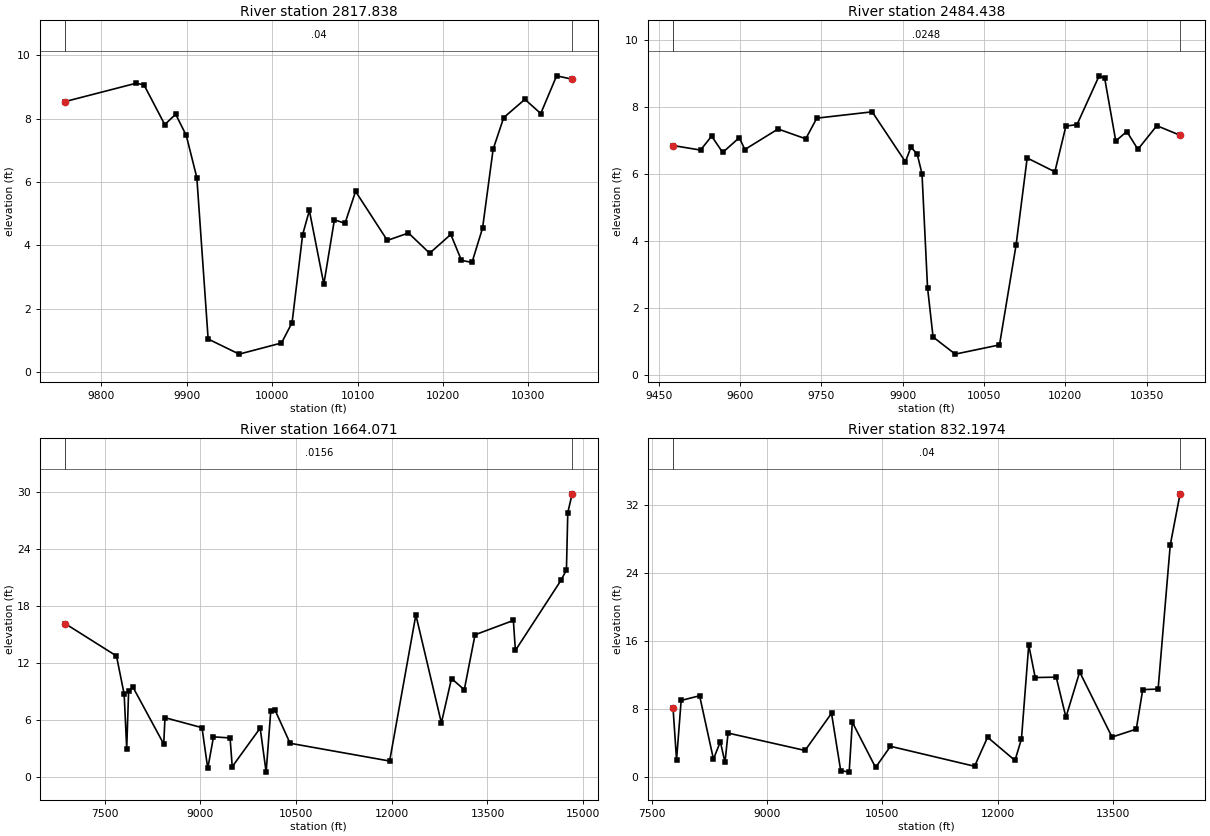
Type RM Length L Ch R = 1 ,2817.838,333.399800,333.399800,333.399800
XS GIS Cut Line= 2
867410.546791731855253.885764613867889.662881012854903.278517458
#Sta/Elev= 30
9757.5318.5369769840.3129.112774 9849.799.0667299874.1787.8104019886.9658.136984
9899.3567.4680059911.7486.1358389924.9791.0436289961.3140.56679810010.880.918333
10023.271.56076710035.664.34050810043.515.09937910060.452.77565110072.844.806995
10085.23 4.6944110097.625.701512 10134.84.15513510159.584.38939210184.36 3.75098
10209.14 4.3448910221.543.52739610233.93 3.4593910246.324.54375310258.717.033724
 10271.18.03151610295.898.60706810314.458.15941410333.06 9.3490910351.239.242472
#Mann= 3 , 0 , 0
9757.531    0.04       09757.531    0.04       010351.23    0.04       0
#XS Ineff= 2 , 0
       0                10090.92       0
Bank Sta=9757.531,10351.23
Exp/Cntr=0.3,0.1

Type RM Length L Ch R = 1 ,2484.438,820.367700,820.367700,820.367700
XS GIS Cut Line= 2
867325.323199156855456.624805159868241.174264175855266.271023043
#Sta/Elev= 30
9476.4676.8596799527.2056.7234459547.6337.140752 9568.066.6518679598.7017.095087
9608.9156.7402869670.1977.3541029721.2667.0602559741.6937.6781169843.8317.867144
9905.1136.3741729915.3276.8060389926.7246.6126729935.7546.0177069945.9682.615292
9956.1811.1355289997.0360.62363310078.750.89956610109.393.89036910129.81 6.48774
10180.886.07363710201.317.44115610221.747.48439610262.598.94327510272.818.872526
10293.23 6.9965110313.667.27796510334.096.745826   10369 7.4525810411.897.166805
#Mann= 3 , 0 , 0
9476.467  0.0248       09476.467  0.0248       010411.89  0.0248       0
#XS Ineff= 2 , 0
       0                10194.97       0
Bank Sta=9476.467,10411.89
Exp/Cntr=0.3,0.1

Type RM Length L Ch R = 1 ,1664.071,831.873300,831.873300,831.873300
XS GIS Cut Line= 6
865230.221540396856164.838615432867841.910685406 856116.31284825
868140.825204689 856055.88034859 868666.65629129855904.063361352
872298.139227581854693.944353685872908.743010627854458.491565507
#Sta/Elev= 30
 6880.7916.140277685.70812.728337805.7298.7040857845.7352.9537057875.7419.034962
7945.7539.4182768425.8363.4549128445.8396.2273189025.9395.1760769115.9550.876371
 9205.974.2078839466.0154.0944319499.5551.0643979937.5485.13250910031.220.491499
10104.086.98109510166.537.086727 10406.73.53125911966.711.65978412377.7917.05502
12777.875.67464112936.4410.3563913136.719.17345113305.3614.9637513906.1816.47292
 13937.8 13.314414651.9320.6943514737.6821.7985314759.1127.8339814827.4329.81448
#Mann= 3 , 0 , 0
 6880.79  0.0156       0 6880.79  0.0156       014827.43  0.0156       0
#XS Ineff= 2 , 0
       09929.693        10130.78       0
Bank Sta=6880.79,14827.43
Exp/Cntr=0.3,0.1

Type RM Length L Ch R = 1 ,832.1974,0.000000,0.000000,0.000000
XS GIS Cut Line= 6
866309.582314902856856.528878352867904.167640405856886.026541855
868361.742890099856813.839364312868893.974797544856594.475227879
870007.891211512856155.924572394872636.602855142855298.257848179
#Sta/Elev= 30
7777.4538.0644337822.8781.9504957882.8888.9716988122.9299.523217 8302.962.050405
8392.9764.1088378452.9861.6530428492.9935.1221079494.6373.0707829839.0687.449739
9958.0450.70447710068.680.51604510109.476.40501110412.311.06367410605.763.562097
11699.981.20704911869.254.63072912225.921.89199912310.074.43664912404.7415.51608
12488.8911.6723112762.3711.71762 12888.6 6.9895413067.42 12.325613488.174.651145
13803.745.58839713887.8910.2507214087.7410.3112614245.5327.2839814373.4433.34008
#Mann= 3 , 0 , 0
7777.453    0.04       07777.453    0.04       014373.44    0.04       0
#XS Ineff= 2 , 0
       09911.085        10111.27       0
Bank Sta=7777.453,14373.44
Exp/Cntr=0.3,0.1